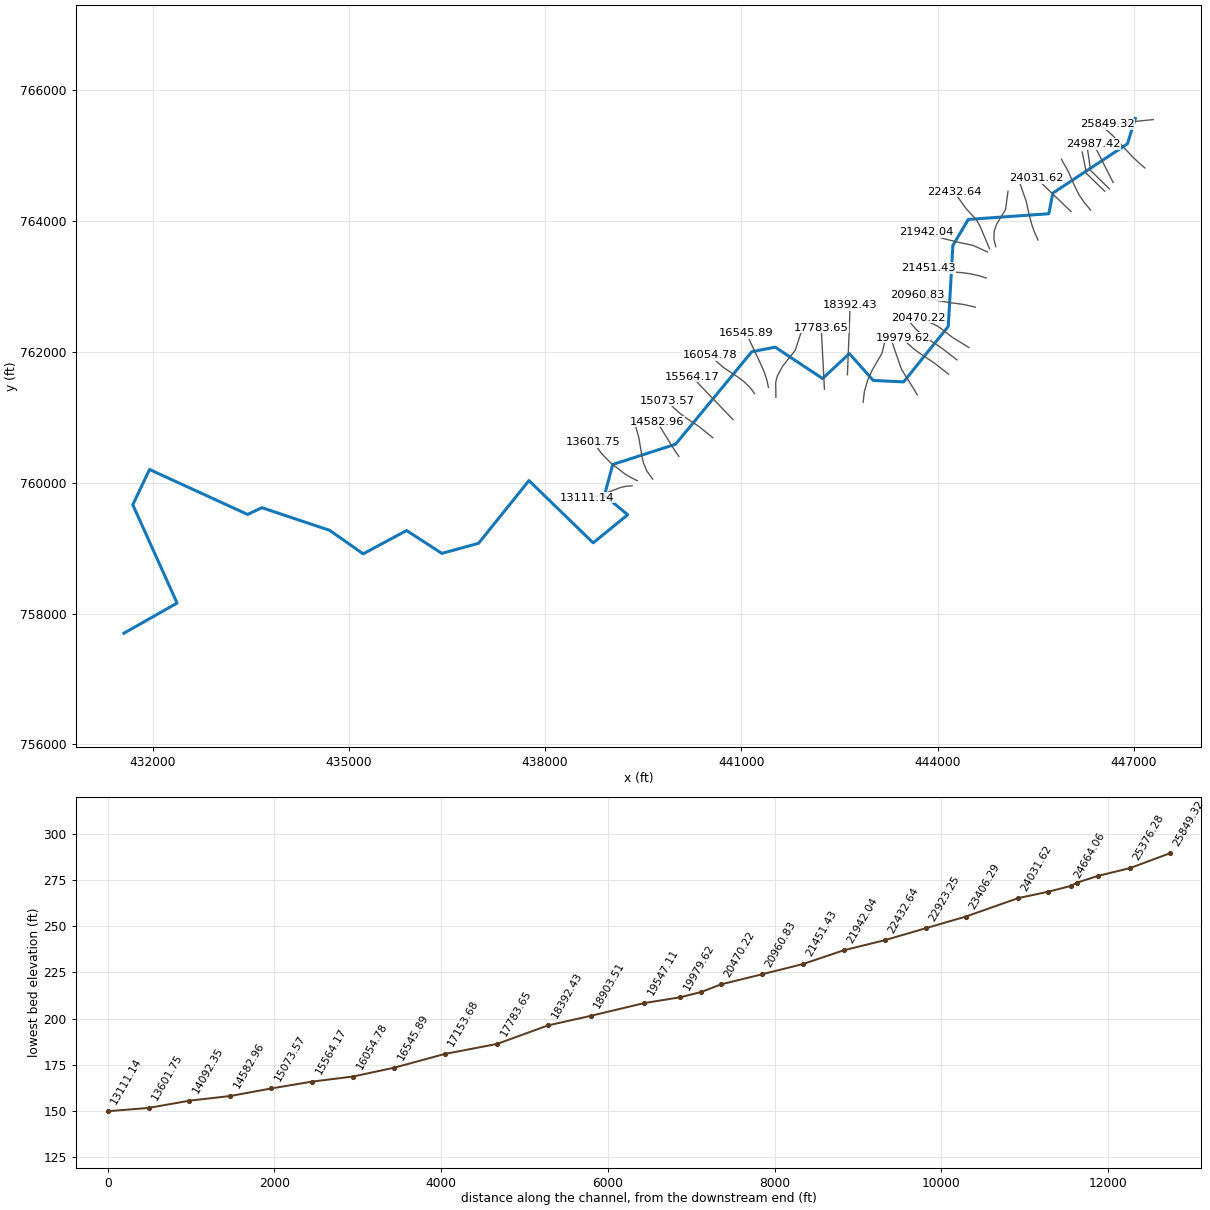
--- 2742_ras.prj (project) ---

Proj Title=2742
Current Plan=p01
Default Exp/Contr=0.3,0.1
English Units
Geom File=g01
Flow File=f01
Plan File=p01
Y Axis Title=Elevation
X Axis Title(PF)=Main Channel Distance
X Axis Title(XS)=Station
BEGIN DESCRIPTION:
RFD model 2742 exported to HEC-RAS
END DESCRIPTION:

--- 2742_ras.p01 (plan) ---

Plan Title=Plan 01
Program Version=4.10
Short Identifier=Plan 01
Geom File=g01
Flow File=f01
Subcritical Flow
Calc Critical at every XS
Secant Critical Depth

--- 2742_ras.f01 (steady flow) ---

Flow Title=Flow 01
Program Version=5.01
Number of Profiles= 6
Profile Names=10yr,25yr,50yr,100yr,100plus,500yr
River Rch & RM=2742,50,25849.32
 2243.43 3639.36  4968.7    6184 9028.6410965.05
River Rch & RM=2742,50,25376.28
 2276.17 3697.64 5052.94 6294.05 9189.3111152.86
River Rch & RM=2742,50,24987.42
  2279.3 3703.28 5061.16 6304.84 9205.0711171.47
River Rch & RM=2742,50,24741.91
 2286.34 3715.79 5079.22 6328.42  9239.5 11211.6
River Rch & RM=2742,50,24395.06
 2301.61 3743.02 5118.62 6379.94 9314.7211299.48
River Rch & RM=2742,50,24031.62
 2386.78 3897.33 5343.98  6676.9 9748.2711812.67
River Rch & RM=2742,50,23406.29
 2406.96 3933.91 5397.43 6747.36 9851.1411934.11
River Rch & RM=2742,50,22923.25
  2412.6 3944.08 5412.25 6766.85  9879.6 11967.5
River Rch & RM=2742,50,22432.64
 2457.15 4024.16 5528.75  6919.910103.0512228.53
River Rch & RM=2742,50,21942.04
 2460.08 4029.52 5536.61 6930.2910118.2212246.48
River Rch & RM=2742,50,21451.43
 2527.08  4151.1 5714.44 7164.9810460.8712649.16
River Rch & RM=2742,50,20960.83
 2532.48  4161.1 5729.24 7184.7110489.6812683.65
River Rch & RM=2742,50,20470.22
 2651.35 4380.01 6052.21 7614.0811116.5513427.11
River Rch & RM=2742,50,20232.44
 2655.13 4387.07 6062.72 7628.1411137.0813451.71
River Rch & RM=2742,50,19979.62
 2659.88 4395.95 6075.93 7645.82 11162.913482.65
River Rch & RM=2742,50,19547.11
 2672.36 4419.33 6110.75 7692.4811231.0213564.42
River Rch & RM=2742,50,18903.51
 2678.56 4430.96  6128.1 7715.7411264.9913605.23
River Rch & RM=2742,50,18392.43
 2738.17 4541.04 6290.85 7932.5511581.5313979.39
River Rch & RM=2742,50,17783.65
 2751.92 4566.77 6329.17 7983.9111656.5114068.96
River Rch & RM=2742,50,17153.68
 2809.77 4673.36 6486.62 8193.5211962.5414428.57
River Rch & RM=2742,50,16545.89
 2822.62 4697.29 6522.17 8241.0812031.9814510.85
River Rch & RM=2742,50,16054.78
 2856.13  4759.4 6614.23 8364.0112211.4614722.36
River Rch & RM=2742,50,15564.17
 2861.64 4769.64 6629.46 8384.3812241.1914757.49
River Rch & RM=2742,50,15073.57
 2873.92 4792.56 6663.55 8430.0412307.8514836.42
River Rch & RM=2742,50,14582.96
  2904.8 4849.83 6748.48 8543.5112473.5315031.29
River Rch & RM=2742,50,14092.35
 2913.34 4865.76  6772.2  8575.312519.9315086.16
River Rch & RM=2742,50,13601.75
 2927.14 4891.43 6810.34 8626.3412594.4615173.97
River Rch & RM=2742,50,13111.14
  2929.7 4896.22 6817.48  8635.912608.4215190.47
River Rch & RM=2742,50,12620.54
 2980.88 4992.08 6960.48 8827.8912888.7215522.37
River Rch & RM=2742,50,12351.73
 2982.08 4994.34 6963.84 8832.3912895.2915530.12
River Rch & RM=2742,50,12256.65
 2982.62 4995.33 6965.33 8834.3912898.2115533.56
River Rch & RM=2742,50,12093.58
 3002.01 5031.89 7020.06  8908.113005.8315661.56
River Rch & RM=2742,50,11634.22
 3015.89 5057.99 7059.08 8960.5813082.4515752.37
River Rch & RM=2742,50,11174.86
 3021.08 5067.69 7073.54 8979.9813110.7715785.73
River Rch & RM=2742,50,10412.54
 3199.22 5394.01 7554.59 9619.6914044.7516859.17
River Rch & RM=2742,50,9796.781
 3229.12 5449.29 7636.52 9729.1514204.5717043.75
River Rch & RM=2742,50,9337.422
 3234.52 5459.34 7651.48  9749.214233.8417077.75
River Rch & RM=2742,50,8878.062
 3261.06 5508.59 7724.63 9847.12 14376.817243.24
River Rch & RM=2742,50,8418.703
 3263.79 5513.69 7732.24 9857.3314391.7117260.58
River Rch & RM=2742,50,7959.344
 3269.76 5524.76 7748.67 9879.3314423.8217297.71
River Rch & RM=2742,50,7499.985
 3288.26 5559.17 7799.88 9947.9714524.0317413.86
River Rch & RM=2742,50,6891.235
  3303.8 5588.03 7842.7810005.4214607.9117510.84
River Rch & RM=2742,50,6581.266
 3308.75 5597.25 7856.5110023.84 14634.817542.02
River Rch & RM=2742,50,6491.053
 3310.45 5600.42 7861.2210030.1514644.0117552.68
River Rch & RM=2742,50,6037.461
 3325.07 5627.47 7901.35 10083.814722.36 17642.8
River Rch & RM=2742,50,5663.381
 3332.99 5642.15 7923.1510112.9814764.9517691.88
River Rch & RM=2742,50,5146.715
 3335.37 5646.57  7929.710121.7414777.74 17706.6
Boundary for River Rch & Prof#=2742,50,1
Up Type= 0
Dn Type= 2
Boundary for River Rch & Prof#=2742,50,2
Up Type= 0
Dn Type= 2
Boundary for River Rch & Prof#=2742,50,2
Up Type= 0
Dn Type= 2
Boundary for River Rch & Prof#=2742,50,2
Up Type= 0
Dn Type= 2
Boundary for River Rch & Prof#=2742,50,2
Up Type= 0
Dn Type= 2
Boundary for River Rch & Prof#=2742,50,2
Up Type= 0
Dn Type= 2

--- 2742_ras.g01 (geometry) ---

Geom Title=2742
Program Version=4.10

River Reach=2742,50
Reach XY= 30
447023.374093145765571.055740073446904.351003826765183.834618121
445763.101003826764429.529062614445701.767670512764114.417951539
444470.795448273764027.890173689444234.962115139763629.140173659
 444164.68501246762392.898019224443482.253781796 761543.30684039
443017.253781617 761565.80684045442652.253781736761976.223507047
442242.670448333761594.973507047441518.503781617762074.556840375
441160.170448273762004.556840345439995.170448273760590.390173718
439034.306921542760280.576503053438907.670448273759808.306840345
 439263.08711496759512.056840315438735.431338489759082.785033926
437753.503781736 760034.55684036 436983.08711499 759075.80684036
436422.253781706758921.640173733435882.670448482 759270.80684036
435218.920448273 758914.55684036 434708.08711496 759273.30684042
433670.103065938759620.577934459433452.325288236759516.827934474
431952.603066444760204.327934444431696.491954833759665.439045638
 432373.71417734758161.550156683431559.984791636757700.639230803

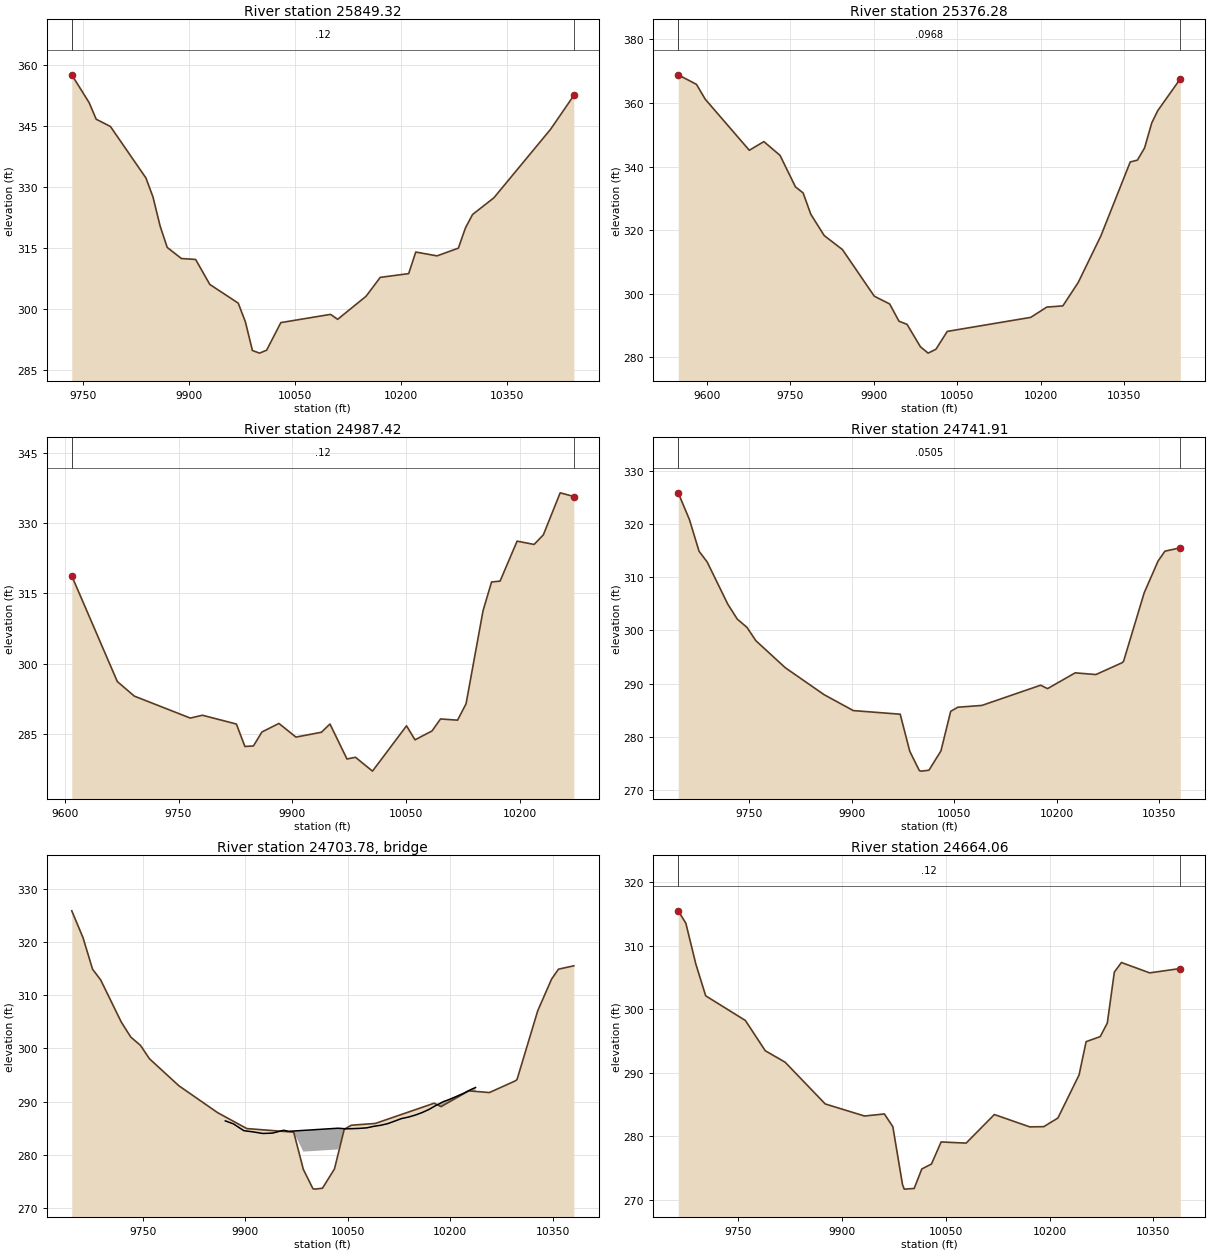
Type RM Length L Ch R = 1 ,25849.32,473.047600,473.047600,473.047600
XS GIS Cut Line= 2
447299.415759802 765554.12865676446592.384509772765482.514073417
#Sta/Elev= 30
9733.543357.61759758.084350.80019768.135 346.7119788.237344.93349838.493332.2894
9848.544327.59649858.595320.47429868.647315.22719888.749312.49989908.851312.2715
9928.954306.13069969.158301.54599979.209296.98949989.261289.91019999.312289.2644
10009.36289.991510029.47296.758410099.82298.788110109.87297.567710150.08303.2269
10170.18307.871610210.39308.792610220.44 314.09410250.59313.150110280.74 315.051
 10290.8320.033110300.85323.3155   10331327.410210411.41344.275910444.19352.5626
#Mann= 3 , 0 , 0
9733.543    0.12       09733.543    0.12       010444.19    0.12       0
#XS Ineff= 2 , 0
       0                               0
Bank Sta=9733.543,10444.19
Exp/Cntr=0.3,0.1

Type RM Length L Ch R = 1 ,25376.28,388.856500,388.856500,388.856500
XS GIS Cut Line= 6
447171.653875006764813.570616856447073.627978839 764898.16324444
446977.538012879764989.865593059 446678.80540302765309.392021378
446618.352730889765364.838691855446525.183921449765440.607466523
#Sta/Elev= 30
 9549.04368.8607 9581.84365.85599597.455361.21399676.707345.13729702.906347.8579
9731.915343.53179759.561333.63589773.384331.72129787.207325.00429811.345318.2965
9844.033313.90039901.271 299.2349928.884296.8002 9945.56291.37959960.064290.3834
9984.109283.34029997.915281.3356 10011.9282.548810032.32288.169510182.36292.5846
10211.14295.816310239.92296.191110267.57303.556810308.28318.209810360.97341.4486
10373.86342.030210386.75345.871910399.64353.726410410.37357.576410450.96367.5974
#Mann= 3 , 0 , 0
 9549.04  0.0968       0 9549.04  0.0968       010450.96  0.0968       0
#XS Ineff= 2 , 0
       0                               0
Bank Sta=9549.04,10450.96
Exp/Cntr=0.3,0.1

Type RM Length L Ch R = 1 ,24987.42,245.508200,245.508200,245.508200
XS GIS Cut Line= 2
446685.490124136764591.445872813446386.879013062 765181.72365059
#Sta/Elev= 30
9609.378318.74139669.395296.19389691.809 293.0849765.535288.39669781.463289.0044
 9826.29287.12749837.497282.33749848.704282.4477 9859.91285.43019882.324 287.252
9904.738284.33659938.358285.37519949.565287.13069971.978279.66469983.185280.0334
 10005.6277.074610050.43286.743110061.63283.756410084.05285.651910095.25288.2127
10117.67287.951110128.87291.441510151.29311.335710162.49317.4393 10173.7  317.63
10196.11326.158510218.53 325.45510230.75327.5184 10252.9336.471210270.89335.6864
#Mann= 3 , 0 , 0
9609.378    0.12       09609.378    0.12       010270.89    0.12       0
#XS Ineff= 2 , 0
       09844.395        10084.32       0
Bank Sta=9609.378,10270.89
Exp/Cntr=0.3,0.1

Type RM Length L Ch R = 1 ,24741.91,77.846100,77.846100,77.846100
XS GIS Cut Line= 3
446626.719146132764495.290635541446341.486941278   764775.813639
446292.517757297765107.269802198
#Sta/Elev= 30
9645.702325.93659662.139 320.8859676.165314.93569688.071312.90619718.243304.9611
9732.268302.12129746.294300.58919759.378298.07129802.398292.98169859.207287.9053
9901.991284.90119970.708284.21589984.734277.2238 9998.76273.582810001.82273.4898
10012.79273.663210030.34277.2969 10044.6284.753310055.05 285.53410090.15285.8677
10176.35 289.68210186.46289.0377 10226.9292.008410257.22291.689910295.41293.9091
10297.66 294.15910327.98307.1106 10348.2313.065610358.31314.939810380.82315.5751
#Mann= 3 , 0 , 0
9645.702  0.0505       09645.702  0.0505       010380.82  0.0505       0
#XS Ineff= 2 , 0
       09960.109        10044.23       0
Bank Sta=9645.702,10380.82
Exp/Cntr=0.3,0.1

Type RM Length L Ch R = 3 ,24703.78,,,
BEGIN DESCRIPTION:
END DESCRIPTION:
Bridge Culvert--1,0,-1,-1, 0
Deck Dist Width WeirC Skew NumUp NumDn MinLoCord MaxHiCord MaxSubmerge Is_Ogee
22.923050,32.000000,2.6,0, 45, 45, , , 0.95, 0, 0,0,,
 9870.54 9870.61 9882.71 9884.32 9897.33 9898.03 9911.74 9911.95 9925.45 9926.57
 9939.16 9941.19 9952.87 9955.81 9963.59 9970.22 9970.2210035.5210040.2210040.22
10042.6210046.4010047.2110057.3510067.4910077.6210087.7610097.8910107.5510108.03
10118.1710128.3010138.4410148.5810158.7110168.7010168.8510178.9910189.1210199.26
10209.4010219.5310229.6710229.8510236.90
  286.35  286.35  285.77  285.62  284.53  284.50  284.27  284.26  283.98  283.98
  284.04  284.10  284.49  284.58  284.39  284.44  284.44  284.97  284.93  284.93
  284.90  284.87  284.86  284.89  284.94  285.04  285.32  285.52  285.80  285.82
  286.29  286.78  287.06  287.44  287.92  288.51  288.52  289.26  289.94  290.43
  290.99  291.56  292.23  292.24  292.64
 -713.65 -713.65 -714.23 -714.38 -715.47 -715.50 -715.73 -715.74 -716.02 -716.02
 -715.96 -715.90 -715.51 -715.42 -715.61 -715.56  280.44  280.97  280.93 -715.07
 -715.10 -715.13 -715.14 -715.11 -715.06 -714.96 -714.68 -714.48 -714.20 -714.18
 -713.71 -713.22 -712.94 -712.56 -712.08 -711.49 -711.48 -710.74 -710.06 -709.57
 -709.01 -708.44 -707.77 -707.76 -707.36
 9870.54 9870.61 9882.71 9884.32 9897.33 9898.03 9911.74 9911.95 9925.45 9926.57
 9939.16 9941.19 9952.87 9955.81 9963.59 9968.33 9968.3310035.5210038.3310038.33
10042.6210046.4010047.2110057.3510067.4910077.6210087.7610097.8910107.5510108.03
10118.1710128.3010138.4410148.5810158.7110168.7010168.8510178.9910189.1210199.26
10209.4010219.5310229.6710229.8510236.90
  286.35  286.35  285.77  285.62  284.53  284.50  284.27  284.26  283.98  283.98
  284.04  284.10  284.49  284.58  284.39  284.43  284.43  284.97  284.94  284.94
  284.90  284.87  284.86  284.89  284.94  285.04  285.32  285.52  285.80  285.82
  286.29  286.78  287.06  287.44  287.92  288.51  288.52  289.26  289.94  290.43
  290.99  291.56  292.23  292.24  292.64
 -713.65 -713.65 -714.23 -714.38 -715.47 -715.50 -715.73 -715.74 -716.02 -716.02
 -715.96 -715.90 -715.51 -715.42 -715.61 -715.57  280.43  280.97  280.94 -715.06
 -715.10 -715.13 -715.14 -715.11 -715.06 -714.96 -714.68 -714.48 -714.20 -714.18
 -713.71 -713.22 -712.94 -712.56 -712.08 -711.49 -711.48 -710.74 -710.06 -709.57
 -709.01 -708.44 -707.77 -707.76 -707.36
BR Coef=-1 , 0 , 0 ,, 0 ,,,0.8,0,1,0,
WSPro=,,,, 1 ,,,, 0 ,,,, 0 ,,,,-1 ,-1 ,-1 , 0 , 0 , 0 , 0 , 0
BC Design=,, 0 ,, 0 ,,,,,,

Type RM Length L Ch R = 1 ,24664.06,268.999700,268.999700,268.999700
XS GIS Cut Line= 3
446557.274701715764457.313205004446278.411854535764728.580566108
446212.222618371765058.441677213
#Sta/Elev= 30
9663.356 315.514 9674.38313.55769688.722307.15789703.063302.12259760.429298.2345
9789.112293.47169817.795291.66389875.793285.08549932.527283.1859 9961.21283.5113
9973.449281.50319987.399272.39949989.893271.666110004.23271.7675 10015.3 274.842
10029.25275.6196 10043.2279.099510079.34278.916110120.14283.4176 10171.4 281.472
10191.53 281.50910211.93282.864710242.53289.653510252.73294.901310273.13 295.699
10283.33297.825210293.53305.862610303.73307.372710344.52 305.73810388.83306.4244
#Mann= 3 , 0 , 0
9663.356    0.12       09663.356    0.12       010388.83    0.12       0
#XS Ineff= 2 , 0
       09965.641         10047.2       0
Bank Sta=9663.356,10388.83
Exp/Cntr=0.3,0.1

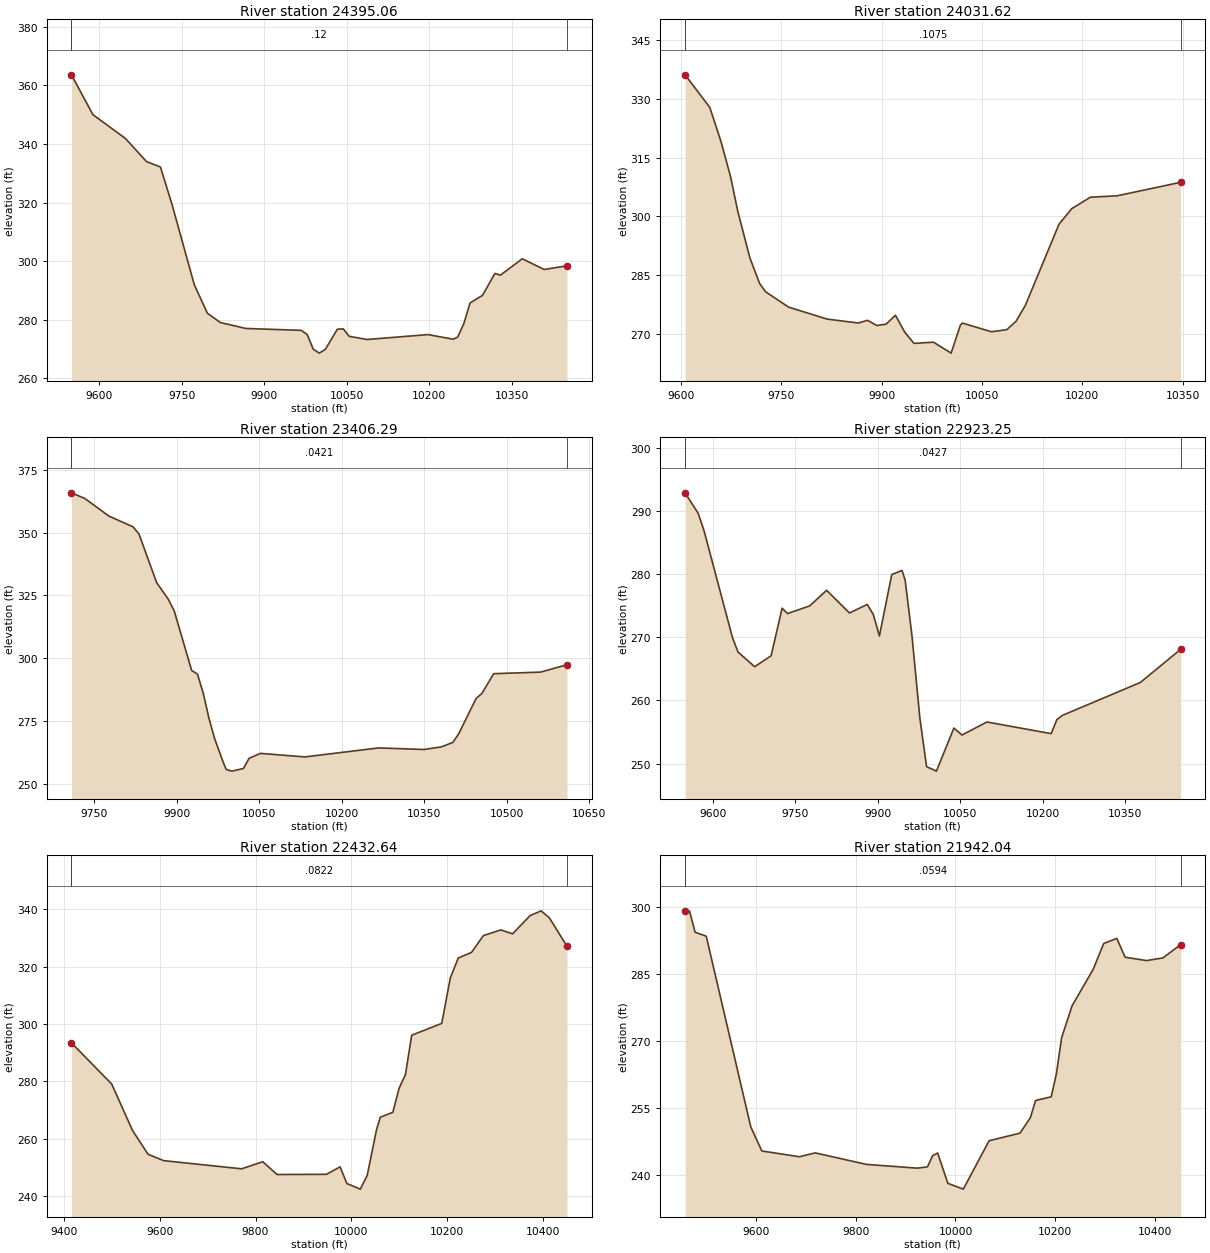
Type RM Length L Ch R = 1 ,24395.06,363.445100,363.445100,363.445100
XS GIS Cut Line= 6
446340.389157599764170.184214095446241.741718663764288.771383285
446162.206045705764406.271564118446088.812186542764554.446430186
446003.148545456764752.214173836445894.073141245764948.605316097
#Sta/Elev= 30
 9549.05363.59579588.111 349.997 9647.42341.85619685.738333.96099711.019332.1323
9731.865319.4925 9772.76291.86159796.496282.18749820.141279.00939866.524276.9923
9967.059  276.359978.094274.95549989.128 269.91310000.19268.5689 10011.3269.8849
10032.95276.729510043.77276.859510054.59 274.30510087.06273.225810198.06274.8944
10243.78273.326210252.01274.035210263.31278.6858 10274.6 285.725 10297.2 288.286
10319.79295.767210329.76295.184710369.55300.794110409.34297.132910450.97298.3779
#Mann= 3 , 0 , 0
 9549.05    0.12       0 9549.05    0.12       010450.97    0.12       0
#XS Ineff= 2 , 0
       09787.065        10181.76       0
Bank Sta=9549.05,10450.97
Exp/Cntr=0.3,0.1

Type RM Length L Ch R = 1 ,24031.62,625.329300,625.329300,625.329300
XS GIS Cut Line= 2
446041.603259772 764147.87865676445507.749093115764660.899490088
#Sta/Elev= 30
9606.435336.18829643.331327.86969660.009 319.1719674.441310.13439684.938301.4804
9703.306289.38169717.738282.88859726.545280.77539761.034276.83569818.763273.7664
9865.234272.77479879.103273.45279892.972272.13029906.841272.4858 9920.71274.7548
9934.579270.44679948.448267.56269977.516267.871310003.92265.074910017.79272.2304
10020.81 272.75510064.11270.534910087.14271.070710101.01 273.23410114.87277.2941
10165.13298.018610184.22302.000710211.96304.916210251.73305.268110346.83308.7243
#Mann= 3 , 0 , 0
9606.435  0.1075       09606.435  0.1075       010346.83  0.1075       0
#XS Ineff= 2 , 0
       09893.524         10037.7       0
Bank Sta=9606.435,10346.83
Exp/Cntr=0.3,0.1

Type RM Length L Ch R = 1 ,23406.29,483.041300,483.041300,483.041300
XS GIS Cut Line= 6
445536.744829203763713.119719203445484.926118549763827.753307226
445444.385701894763939.644562835 445407.75302891764070.263317377
445356.226132891 764305.25650244445263.403939112764570.071544045
#Sta/Elev= 30
9708.134365.8058 9732.39363.5742 9776.57356.53159820.088352.30039830.967349.4654
9863.156 330.1389884.585323.4272 9895.21318.85179926.932295.17059937.506293.7129
 9948.08286.06959958.587276.02129969.035267.84899985.382258.13549989.931255.7806
10000.38255.143510021.21256.207210031.55260.258710052.22262.205410132.97260.7938
10267.28 264.37210350.07263.743910381.53264.784610402.51266.583210412.99270.0128
10444.66284.031310455.32 286.08910476.65293.886610561.98294.516910610.05 297.447
#Mann= 3 , 0 , 0
9708.134  0.0421       09708.134  0.0421       010610.05  0.0421       0
#XS Ineff= 2 , 0
       0                10274.09       0
Bank Sta=9708.134,10610.05
Exp/Cntr=0.3,0.1

Type RM Length L Ch R = 1 ,22923.25,490.605300,490.605300,490.605300
XS GIS Cut Line= 6
444890.126735816763612.223233686444861.793295985763728.606108824
444867.756782929763853.034366742444904.206995284763955.707152936
445040.793320225764178.957076869445077.719931342764458.344689413
#Sta/Elev= 30
9549.165292.8334 9573.11289.57189583.623286.84119635.274269.97049645.392267.6598
9675.642265.33129705.663267.05669725.676274.58389735.696273.73739776.009274.9593
9806.661 277.4169848.246273.82979880.627275.17869891.668273.58229902.709270.1822
9925.229279.91229943.933280.56019949.558279.02229961.995270.21149976.351257.2019
9988.553249.526210006.48248.815710038.24255.6239   10053254.524610098.31256.5868
10215.25254.748310225.64 256.96410236.03257.645410377.47262.831910450.82268.0778
#Mann= 3 , 0 , 0
9549.165  0.0427       09549.165  0.0427       010450.82  0.0427       0
#XS Ineff= 2 , 0
       09945.732        10228.61       0
Bank Sta=9549.165,10450.82
Exp/Cntr=0.3,0.1

Type RM Length L Ch R = 1 ,22432.64,490.605200,490.605200,490.605200
XS GIS Cut Line= 6
444796.811593145763577.566156745444648.828679174763926.468460739
444605.610992908764004.409340173 444571.12787661764048.851545095
444438.077569306764191.445212692444254.000690311764448.362786606
#Sta/Elev= 30
9415.254293.43049499.388279.0669 9542.85262.87579575.446254.51779608.042252.3102
9770.931249.45339815.044251.92439845.171247.46319948.353247.53689976.754250.1432
9990.942244.317710018.93242.364510033.37247.131310052.79263.027910060.74267.4543
   10087269.199910100.13277.620410113.27282.3324 10126.4296.104810189.17300.2132
10206.97316.028710223.71323.051510251.52325.030810276.23330.8803 10312.8332.8709
10337.17331.489310373.73337.842310396.72 339.52910414.22337.076910450.95327.1369
#Mann= 3 , 0 , 0
9415.254  0.0822       09415.254  0.0822       010450.95  0.0822       0
#XS Ineff= 2 , 0
       09844.593                       0
Bank Sta=9415.254,10450.95
Exp/Cntr=0.3,0.1

Type RM Length L Ch R = 1 ,21942.04,490.605200,490.605200,490.605200
XS GIS Cut Line= 6
444762.957426429763530.691156745444544.090924442763630.291442752
444280.823116601 763686.66706726444091.515705287 763735.34312664
443953.108372271763780.049019441443822.461541891763834.259115756
#Sta/Elev= 30
9458.425299.17249467.303 299.1249478.459294.39279500.773293.49489590.027250.8535
9612.148245.45989687.494244.17859718.993 245.0359821.854242.46199923.603241.6209
9943.952241.91889954.127 244.4089964.302245.00719984.806238.218210015.71236.9323
 10067.4247.757410129.41249.458510150.09252.934910160.42256.757210191.72257.5793
10202.16262.7377 10212.6270.786410233.49 277.91510275.77286.078310296.93291.8671
10323.16293.009510339.66288.803210382.74288.044410415.47 288.63810450.98291.6143
#Mann= 3 , 0 , 0
9458.425  0.0594       09458.425  0.0594       010450.98  0.0594       0
#XS Ineff= 2 , 0
       09718.738                       0
Bank Sta=9458.425,10450.98
Exp/Cntr=0.3,0.1

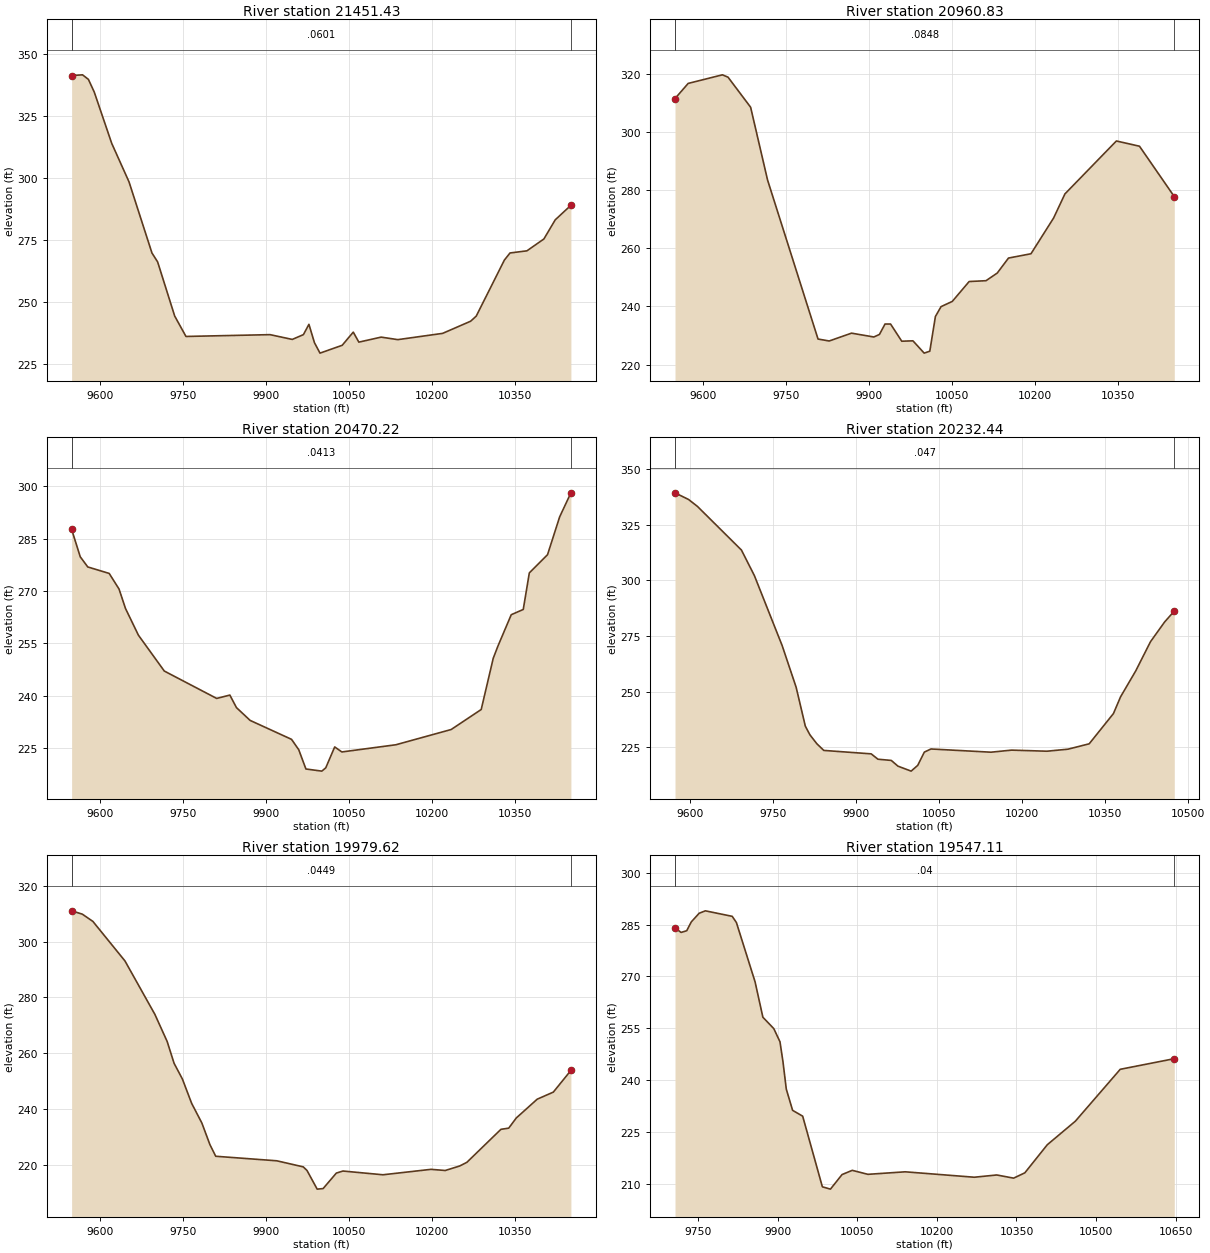
Type RM Length L Ch R = 1 ,21451.43,490.605300,490.605300,490.605300
XS GIS Cut Line= 6
444743.592359121763132.024564663444625.680633924763169.644304908
444504.882869792763195.864539362444381.851183854763212.906606024
444148.551718946763231.454622039443857.437534946763284.867997479
#Sta/Elev= 30
9549.034341.20259568.743341.48029579.344339.64659589.945334.53039621.452313.9069
9652.713298.4083 9694.12269.80879704.407266.20129735.215244.42139755.598236.2055
9907.466236.93279947.643235.01219967.705236.93279977.712 241.0859987.716233.6786
9997.721229.496810037.76232.640610057.82237.946610067.88233.923110108.13235.9324
10138.32234.927110219.21237.441410269.82242.335810279.94 244.38410330.77266.9265
10340.96269.794810371.53270.660810402.17 275.43110422.68283.137310450.96288.9763
#Mann= 3 , 0 , 0
9549.034  0.0601       09549.034  0.0601       010450.96  0.0601       0
#XS Ineff= 2 , 0
       0                               0
Bank Sta=9549.034,10450.96
Exp/Cntr=0.3,0.1

Type RM Length L Ch R = 1 ,20960.83,490.605200,490.605200,490.605200
XS GIS Cut Line= 6
444578.037289716762687.127677282444394.853145186762727.897160888
444168.191204887762758.635293847443934.178921698762799.623214666
443814.094987528762827.846511468443695.474935112762865.623964728
#Sta/Elev= 30
9549.031311.42859572.788316.63789634.656319.59269644.851318.78249685.632308.4526
9716.217283.4565  9807.4228.79599827.565228.12419867.897230.81489908.228229.5007
9918.311230.37079928.394233.94799938.477233.94869958.642228.0454 9978.88228.1814
9999.154223.952310009.31224.612310019.46236.545410029.62239.924310049.93 241.723
10080.39248.555210110.86248.844610131.17251.473410151.48256.6238 10192.1258.1014
10232.95270.382310253.42278.662710346.37296.8597 10388.1295.058910450.98277.7532
#Mann= 3 , 0 , 0
9549.031  0.0848       09549.031  0.0848       010450.98  0.0848       0
#XS Ineff= 2 , 0
       0                               0
Bank Sta=9549.031,10450.98
Exp/Cntr=0.3,0.1

Type RM Length L Ch R = 1 ,20470.22,237.786500,237.786500,237.786500
XS GIS Cut Line= 6
444478.313364719762069.937198569444226.406873106762225.391681127
444057.165465362 762358.22637699444000.816693455762395.949422554
443931.598901347762431.068552961443706.451411951762528.017275668
#Sta/Elev= 30
9549.034287.62439564.585 279.7869578.181276.8767 9616.88275.0241 9634.67270.5656
9646.351265.00449669.712257.36939716.435247.12569811.084239.29999834.858240.2574
9846.812236.67019871.537233.01289946.257227.60889959.264224.6586 9972.27219.1351
   10001218.5235 10008.1219.462410024.25225.432310037.21 224.00310134.69226.0562
10234.65230.4172 10288.9236.1319 10310.6250.754110318.97254.200810343.16263.2235
10364.87264.728510375.82275.1712 10408.7280.373610430.61291.182810450.93298.0591
#Mann= 3 , 0 , 0
9549.034  0.0413       09549.034  0.0413       010450.93  0.0413       0
#XS Ineff= 2 , 0
       0                               0
Bank Sta=9549.034,10450.93
Exp/Cntr=0.3,0.1

Type RM Length L Ch R = 1 ,20232.44,252.818700,252.818700,252.818700
XS GIS Cut Line= 6
444296.711877498761879.618139069444079.351050428762049.380009733
443853.733300196762200.707155018443765.615761553 762265.30654162
443671.956302474762348.072600711443593.044232827762438.486979555
#Sta/Elev= 30
9572.944339.25489597.435336.26639613.357333.18639692.965 313.5759716.341 302.114
9766.483270.72969791.764252.02759808.347234.58559816.625230.69399829.161226.6821
9841.696223.68729927.324222.1462 9939.53219.74029963.667219.19449975.599  216.64
9999.464214.3974 10011.4216.974410023.33222.921410035.27224.334610143.71222.8914
 10180.9223.819110244.84223.332310282.71224.238710321.13226.646610365.01240.2469
10377.86247.752410405.14 259.32710431.91272.470910457.56281.368110474.86286.1943
#Mann= 3 , 0 , 0
9572.944   0.047       09572.944   0.047       010474.86   0.047       0
#XS Ineff= 2 , 0
       09942.265           10204       0
Bank Sta=9572.944,10474.86
Exp/Cntr=0.3,0.1

Type RM Length L Ch R = 1 ,19979.62,432.508500,432.508500,432.508500
XS GIS Cut Line= 6
444169.975766387761660.868139069443952.614939317761830.630009733
443726.997189085761981.957155018443638.879650442 762046.55654162
443545.220191363762129.322600711443466.308121716762219.736979555
#Sta/Elev= 30
 9549.02310.95789568.265309.77429587.442307.17439645.371293.05439699.432273.9657
9721.579264.29129734.115256.49019749.183250.85429765.766242.21879784.257235.1699
9798.933227.40669809.328223.28659919.674221.66449967.502219.49149974.249218.2016
9992.578211.546510003.29211.7359 10027.2217.275210039.16218.009610111.43216.6734
10198.23 218.61310223.91218.2028   10250219.804810263.04221.123410324.55232.9085
 10338.6233.328410352.23 236.95510390.02243.668810419.21246.201810450.94253.9451
#Mann= 3 , 0 , 0
 9549.02  0.0449       0 9549.02  0.0449       010450.94  0.0449       0
#XS Ineff= 2 , 0
       0 9935.03                       0
Bank Sta=9549.02,10450.94
Exp/Cntr=0.3,0.1

Type RM Length L Ch R = 1 ,19547.11,643.595000,643.595000,643.595000
XS GIS Cut Line= 5
443690.916068077761346.163008213443594.306181282761505.217670351
443524.528345585761614.197559863443445.781500518761743.341619715
443292.135667175762191.258286372
#Sta/Elev= 30
9706.922284.07289718.318282.74469728.961283.2357 9737.58285.79639752.362288.2951
9764.062289.00469814.631287.40969822.563285.60839857.663268.46259872.419258.1872
9893.018254.87979904.634251.06329910.277245.26519916.508237.35759928.382231.2186
9947.367229.52489984.458209.06389999.627208.396210021.55212.616110040.73213.8345
10070.21212.682110140.49213.410310270.58211.842610312.87212.496110344.59211.5799
10365.73 213.11110408.02221.247710460.88  228.0710545.45243.102810647.22246.1768
#Mann= 3 , 0 , 0
9706.922    0.04       09706.922    0.04       010647.22    0.04       0
#XS Ineff= 2 , 0
       0                               0
Bank Sta=9706.922,10647.22
Exp/Cntr=0.3,0.1

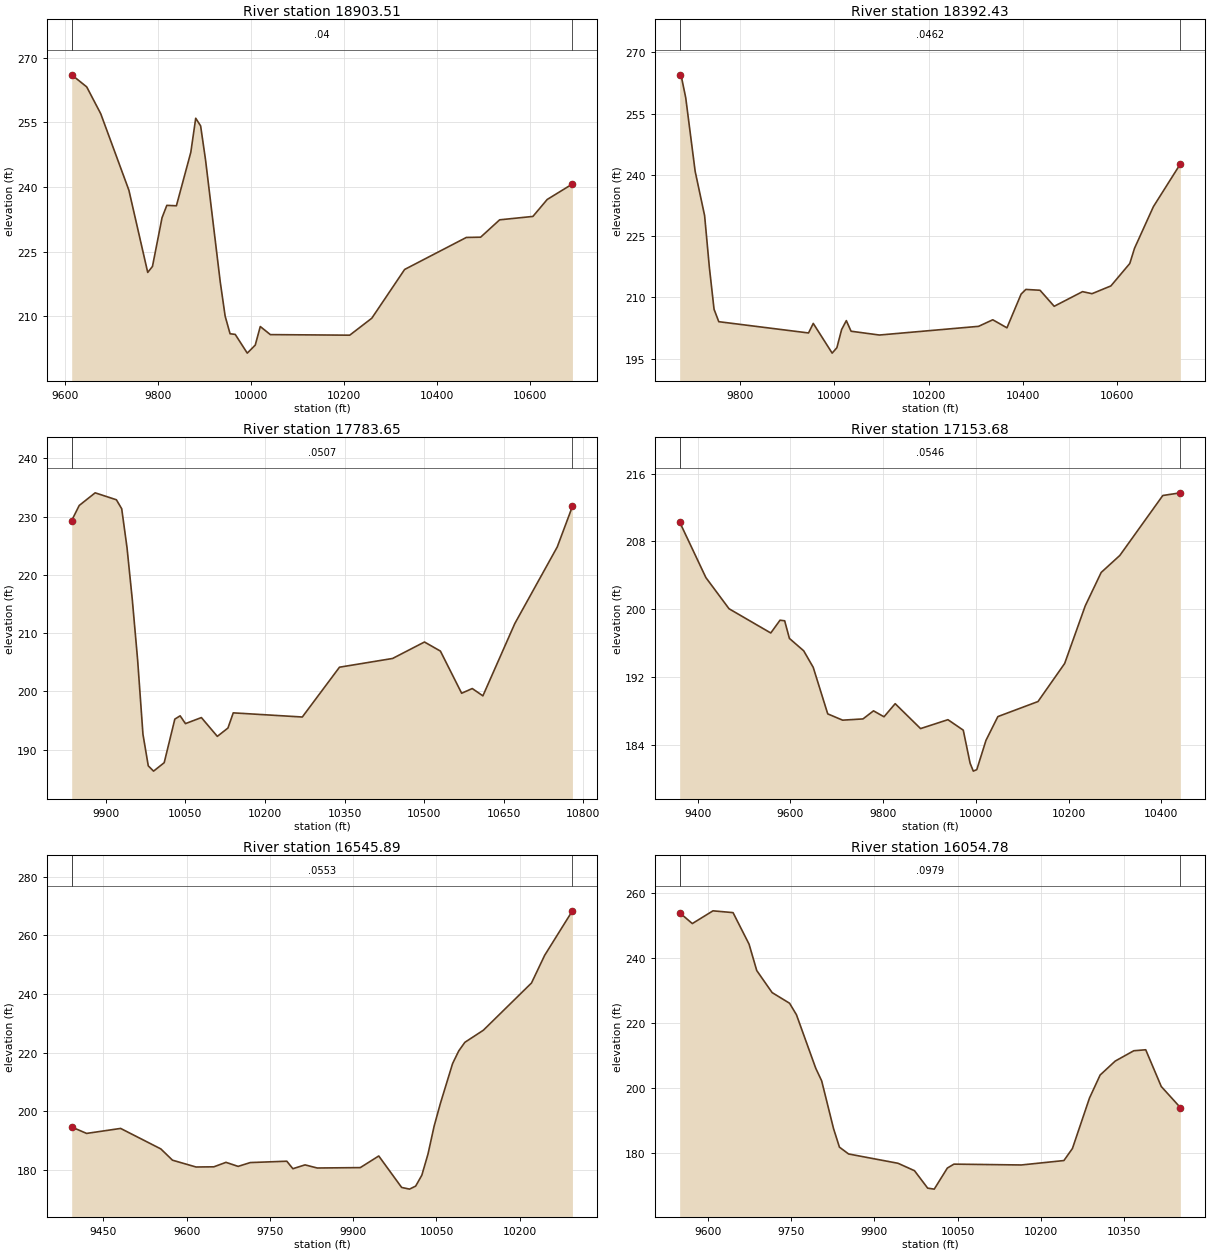
Type RM Length L Ch R = 1 ,18903.51,511.081600,511.081600,511.081600
XS GIS Cut Line= 6
442862.711211354761232.750527993442882.828522056761400.554455459
442931.493502468761566.898340538442997.428730875761716.145972192
443151.948121011761983.196560636443211.406500518762238.133286372
#Sta/Elev= 30
9614.663266.02869647.022263.22129677.124257.00189737.661239.26799778.164220.1914
9788.365221.58599808.955232.88439819.249235.74979839.839235.64989870.828248.0582
9881.382255.95679891.936254.1873 9902.49246.31219934.152217.97589944.706210.0408
 9955.26 205.9689966.343205.82029992.239 201.47410009.41203.335410020.25207.6429
10041.93 205.76810212.62205.636810260.08209.571510330.71220.882610463.41228.3066
10494.17228.368410535.05 232.39510606.59233.182110637.25237.109310691.55240.7039
#Mann= 3 , 0 , 0
9614.663    0.04       09614.663    0.04       010691.55    0.04       0
#XS Ineff= 2 , 0
       0                               0
Bank Sta=9614.663,10691.55
Exp/Cntr=0.3,0.1

Type RM Length L Ch R = 1 ,18392.43,608.784400,608.784400,608.784400
XS GIS Cut Line= 2
442622.864833862761652.195786387442664.531500518762712.091619715
#Sta/Elev= 30
9672.698264.42379675.504264.47399685.512258.89229705.527 240.8439725.543230.0058
 9735.55217.41729745.558207.06189755.566204.02069945.713201.2607 9955.72203.5986
9995.751196.323110005.76197.651710015.77202.092410025.77204.287910035.78201.6859
10095.83200.754510305.99202.884610336.01204.489410366.04  202.5210396.06210.7856
10406.07 211.92210436.09211.719410466.11 207.79310526.16211.380410546.18210.8763
10586.21212.778110626.24218.273210636.25221.990410676.28232.198810733.41242.6574
#Mann= 3 , 0 , 0
9672.698  0.0462       09672.698  0.0462       010733.41  0.0462       0
#XS Ineff= 2 , 0
       0 9830.78        10082.23       0
Bank Sta=9672.698,10733.41
Exp/Cntr=0.3,0.1

Type RM Length L Ch R = 1 ,17783.65,629.965200,629.965200,629.965200
XS GIS Cut Line= 2
442271.302333862  761430.8416197442221.823167175762373.549953058
#Sta/Elev= 30
9835.642229.3261 9849.82231.90269879.861234.07369919.916 232.881 9929.93231.3368
9939.944224.65959949.958215.69029959.971205.36999969.985192.65299979.999187.2364
9990.013 186.33110010.04187.779610030.07195.253210040.08 195.817 10050.1 194.482
10080.14195.517410110.18192.293310130.21193.723110140.22196.3274 10270.4195.6146
10340.49204.158910440.63 205.65810500.71208.481810530.76206.927210570.81199.6916
10590.84200.499910610.87199.244710670.95211.632210751.06224.789410779.65231.7408
#Mann= 3 , 0 , 0
9835.642  0.0507       09835.642  0.0507       010779.65  0.0507       0
#XS Ineff= 2 , 0
       0                               0
Bank Sta=9835.642,10779.65
Exp/Cntr=0.3,0.1

Type RM Length L Ch R = 1 ,17153.68,607.796300,607.796300,607.796300
XS GIS Cut Line= 6
441529.114833862761308.445786392441526.175718158761537.791302656
441551.489724547761633.681597372441633.323657095  761785.0213441
441824.576264888762026.787695323441907.882724255762282.205726375
#Sta/Elev= 30
9361.017 210.2949417.576203.7378 9467.58200.05559557.587 197.1979577.589198.7064
 9587.59198.63479597.791196.5574 9628.63195.09419649.188193.14239680.496187.6508
9712.648186.90899756.555187.05459779.236188.00859801.916187.30819825.997188.8532
9880.783185.91419939.831186.96539972.924185.72689987.615181.83639994.537180.8939
10002.08181.071210021.89184.523510047.54187.330510134.11 189.10610191.67193.5984
10236.01200.393110270.47 204.342 10310.7206.348910403.41213.424510441.32213.7393
#Mann= 3 , 0 , 0
9361.017  0.0546       09361.017  0.0546       010441.32  0.0546       0
#XS Ineff= 2 , 0
       09805.449                       0
Bank Sta=9361.017,10441.32
Exp/Cntr=0.3,0.1

Type RM Length L Ch R = 1 ,16545.89,491.110900,491.110900,491.110900
XS GIS Cut Line= 6
441415.001507035761458.737050735 441397.23104756761544.013031847
441381.470405957761604.984006484441343.628392542761712.120120175
441272.261217575761871.327199417441073.956545145762290.512018875
#Sta/Elev= 30
9392.954194.64849419.781192.46569481.081194.16759553.544187.17299574.524183.3272
9616.941181.00729649.083181.07159670.826182.59519692.743181.21829714.661182.5198
9780.413182.98199791.372180.4246 9813.29181.73049835.252180.66539912.827 180.801
9946.071184.76589987.267174.038910001.48173.458810012.56174.491310023.64 178.201
10034.72185.4052 10045.8194.937810056.88202.570410079.05216.292610090.13220.6028
10101.21223.548710134.45227.663710221.19243.783110244.94 253.23410294.91268.4042
#Mann= 3 , 0 , 0
9392.954  0.0553       09392.954  0.0553       010294.91  0.0553       0
#XS Ineff= 2 , 0
       09658.098                       0
Bank Sta=9392.954,10294.91
Exp/Cntr=0.3,0.1

Type RM Length L Ch R = 1 ,16054.78,490.605300,490.605300,490.605300
XS GIS Cut Line= 6
441202.985916852761366.317932728441129.829124031761461.436179052
441040.036882012761548.334941088440960.793283295761608.819478141
440722.010133147 761767.09651245440520.454160902761947.173473466
#Sta/Elev= 30
9549.071254.01249571.906250.67499609.081254.60649645.234254.05249674.081244.3216
9687.919236.17449715.594229.37759746.995226.09179759.441222.53889794.185206.0247
9804.853202.14239826.249187.39639836.866 181.6799853.363179.57439942.426176.6991
9972.043174.41479995.797169.029210007.62168.726610031.26175.234910043.08176.4387
10164.51176.179810241.17177.545710256.54181.267410287.29  196.8510306.48 203.952
10333.57208.238410367.01211.426810388.53211.731810416.56200.391810450.96193.8876
#Mann= 3 , 0 , 0
9549.071  0.0979       09549.071  0.0979       010450.96  0.0979       0
#XS Ineff= 2 , 0
       09759.788                       0
Bank Sta=9549.071,10450.96
Exp/Cntr=0.3,0.1

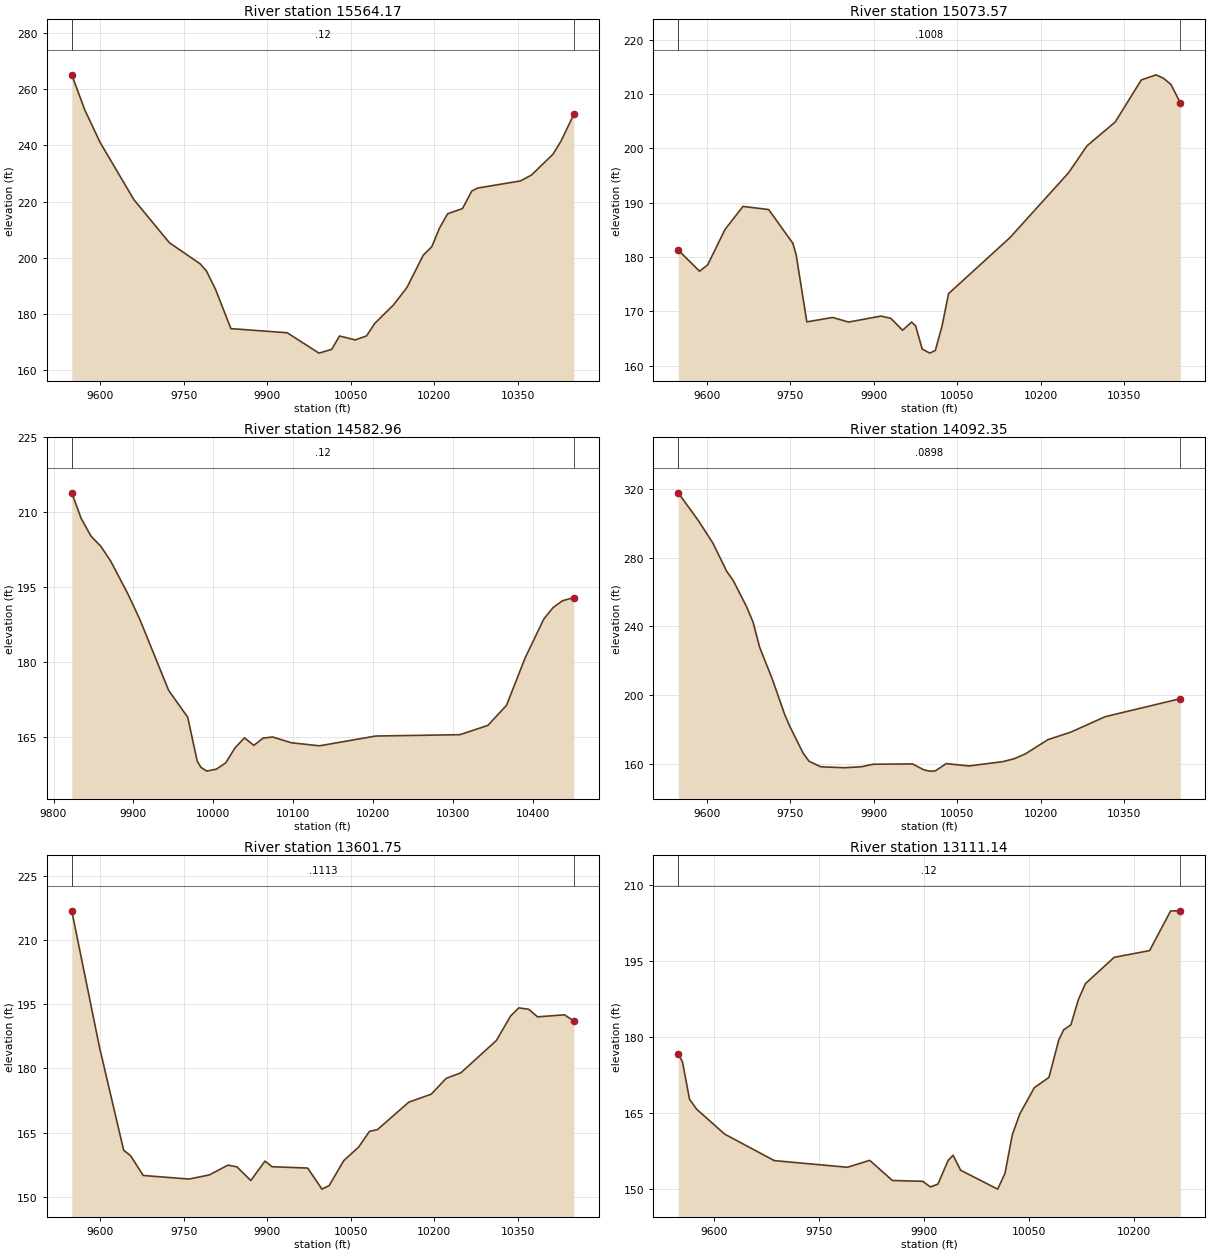
Type RM Length L Ch R = 1 ,15564.17,490.605200,490.605200,490.605200
XS GIS Cut Line= 6
440872.058400024760968.100472227440582.518751036761271.717677699
440560.824083321761293.073053121440559.346926421761294.421388203
440521.257074252 761332.59912323440249.097668642761620.327890447
#Sta/Elev= 30
9549.015265.15949572.367252.68099600.003 241.0519660.672 220.6529724.367205.3214
9779.639197.81059791.083195.21449807.276188.68999834.912174.70299935.983173.2324
 9993.14165.971210015.94167.312410030.07172.075710058.23 170.67510078.59172.0983
10093.14176.534210127.06 183.16310151.35189.430810180.45200.874410195.88203.9371
10209.56210.504310224.11 215.62810250.94217.491210267.77223.789810278.47224.8184
10355.08 227.34210374.83229.437910413.29236.815810427.84 241.49510450.98251.1121
#Mann= 3 , 0 , 0
9549.015    0.12       09549.015    0.12       010450.98    0.12       0
#XS Ineff= 2 , 0
       0                               0
Bank Sta=9549.015,10450.98
Exp/Cntr=0.3,0.1

Type RM Length L Ch R = 1 ,15073.57,490.605300,490.605300,490.605300
XS GIS Cut Line= 6
440564.354192039760691.150262105440345.632223461760866.980920924
440148.427355005760997.190502832440065.445297084761059.273167156
439968.722942417761146.413198807439866.539638375761257.477506812
#Sta/Elev= 30
9549.039181.27979587.265177.38219601.882178.54219633.105185.0743  9665.4189.3196
9711.546188.74189754.877 182.5379760.802180.44569780.094168.04149826.477 168.855
9854.924168.0089  9913.4169.10589930.824168.70239951.956 166.4969968.371168.0079
9975.527167.28239987.312 163.039   10001162.280710010.91162.784510022.77167.1866
10034.62173.245610144.97  183.5710250.23195.519510283.33200.487210334.07 204.884
10380.84  212.6310407.57213.572310420.93212.925610434.29211.775510450.96208.4091
#Mann= 3 , 0 , 0
9549.039  0.1008       09549.039  0.1008       010450.96  0.1008       0
#XS Ineff= 2 , 0
       0                               0
Bank Sta=9549.039,10450.96
Exp/Cntr=0.3,0.1

Type RM Length L Ch R = 1 ,14582.96,490.605200,490.605200,490.605200
XS GIS Cut Line= 6
440045.802901447 760405.37648581439996.830535769760474.074491501
439946.984322369760551.139725819439944.250072479760555.089183435
439803.167606086760785.096084461439712.168709517760937.327844054
#Sta/Elev= 30
9822.853 213.8779834.671208.72779846.952205.20969859.233 203.1769871.514200.2298
9893.145193.63079908.322188.4336 9944.05174.35739967.869 168.9969979.778160.2272
9984.241158.99269991.688 158.20110003.81 158.59710015.44159.856410027.17162.8738
 10038.9164.864310050.63163.354910062.36164.814310074.09165.029610097.56163.8789
10132.75163.264710203.14165.222810308.48165.490310343.43167.347610366.73171.3538
10390.03180.837210413.33188.601410424.98190.912310436.63192.2725   10451192.9342
#Mann= 3 , 0 , 0
9822.853    0.12       09822.853    0.12       0   10451    0.12       0
#XS Ineff= 2 , 0
       0                               0
Bank Sta=9822.853,10451
Exp/Cntr=0.3,0.1

Type RM Length L Ch R = 1 ,14092.35,490.605200,490.605200,490.605200
XS GIS Cut Line= 6
439646.257828865760057.817604059439557.180066935760178.168115248
439506.187696751760298.163348451439481.745992866760399.209331454
439433.810379592760691.226884442439373.173783588760903.853842966
#Sta/Elev= 30
9549.088317.77389585.171301.63539611.072288.65449636.165272.06239648.012266.6212
9671.702251.54379683.548242.43919695.393227.76469718.197209.1515 9740.39 188.598
9749.295  181.899773.301166.20949783.928161.45869805.155158.2098 9847.19157.6628
9878.285158.22639898.792 159.6799969.944 159.8589990.173156.440610000.28155.6744
10010.38155.736210030.58160.0631   10071158.683210131.77161.175510152.13162.8436
 10172.5165.689610213.22174.016210254.25178.383110316.09187.393710450.94197.8728
#Mann= 3 , 0 , 0
9549.088  0.0898       09549.088  0.0898       010450.94  0.0898       0
#XS Ineff= 2 , 0
       0                               0
Bank Sta=9549.088,10450.94
Exp/Cntr=0.3,0.1

Type RM Length L Ch R = 1 ,13601.75,490.605300,490.605300,490.605300
XS GIS Cut Line= 6
 439409.27651325760032.903539393439302.131517191760087.127539358
439213.062139297760141.850518733439002.212241267760306.206076066
 438864.82618593760447.089361165438739.315057702760618.884784409
#Sta/Elev= 30
9549.044216.89129598.667185.08489642.271160.84629654.706159.57649677.392154.9492
9759.452154.1114 9796.12155.07439829.619157.37359845.786156.96029870.618 153.776
9896.159158.31229908.948 156.994 9972.89156.68319998.466151.751510011.41152.5769
10037.47158.404510064.41161.5983 10083.8165.272810098.31165.695710154.36172.1019
 10194.8173.980910221.75 177.69210248.11178.986710311.77 186.54110337.23192.2587
10352.03194.174710369.79 193.85510385.73192.077110434.13192.550810450.93191.1222
#Mann= 3 , 0 , 0
9549.044  0.1113       09549.044  0.1113       010450.93  0.1113       0
#XS Ineff= 2 , 0
       0                               0
Bank Sta=9549.044,10450.93
Exp/Cntr=0.3,0.1

Type RM Length L Ch R = 1 ,13111.14,490.605200,490.605200,490.605200
XS GIS Cut Line= 6
439331.116401196759954.356179044439242.067646205759948.245353013
439156.088063776 759929.71657528438915.031968504 759837.05538708
438781.085199505759795.518362954438641.147380173759775.551774323
#Sta/Elev= 30
9549.083176.70029555.204175.03969565.212167.69959575.219165.76229615.315160.8292
9686.388155.59379790.854154.27719822.774155.64539855.303151.67089898.675151.5099
9909.518150.39389920.361150.95659934.849155.61119942.047156.65479952.776 153.696
10005.75149.968910016.22153.0734 10026.7160.690510037.17164.732210058.11169.9751
10079.05172.002910093.07179.365710099.99181.370110110.47182.378110120.94187.2815
10131.28190.503310172.32195.681810222.97197.010410252.99204.833310266.85204.8508
#Mann= 3 , 0 , 0
9549.083    0.12       09549.083    0.12       010266.85    0.12       0
#XS Ineff= 2 , 0
       0                               0
Bank Sta=9549.083,10266.85
Exp/Cntr=0.3,0.1