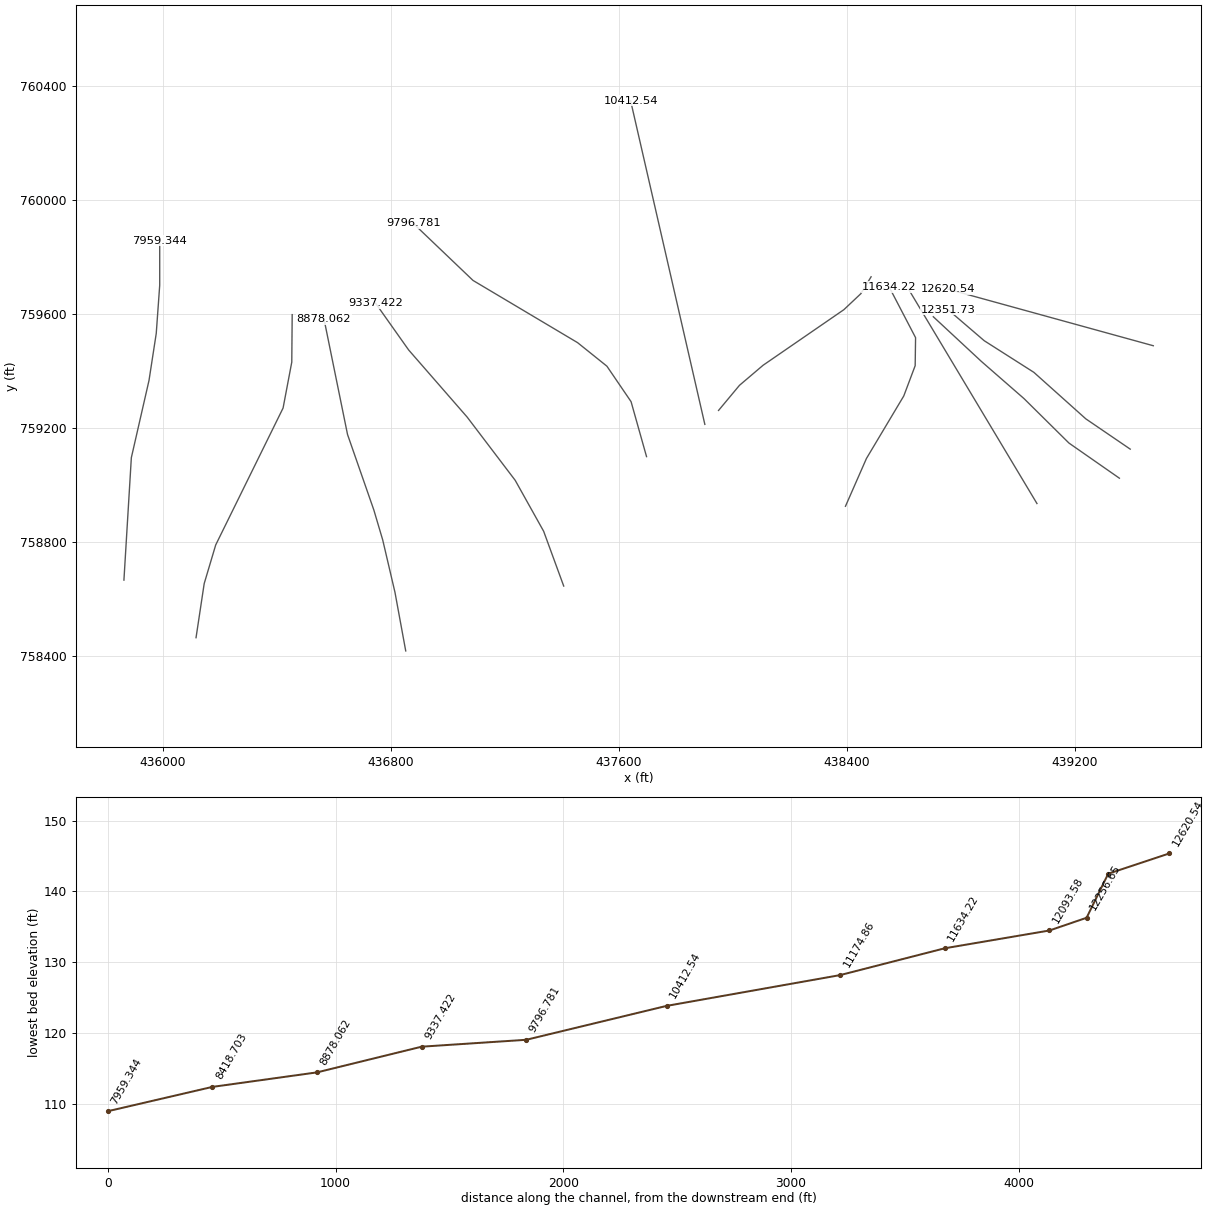
HEC-RAS study 2742_ras.prj: 2742

--- 2742_ras.g01 (geometry) --- (continued)

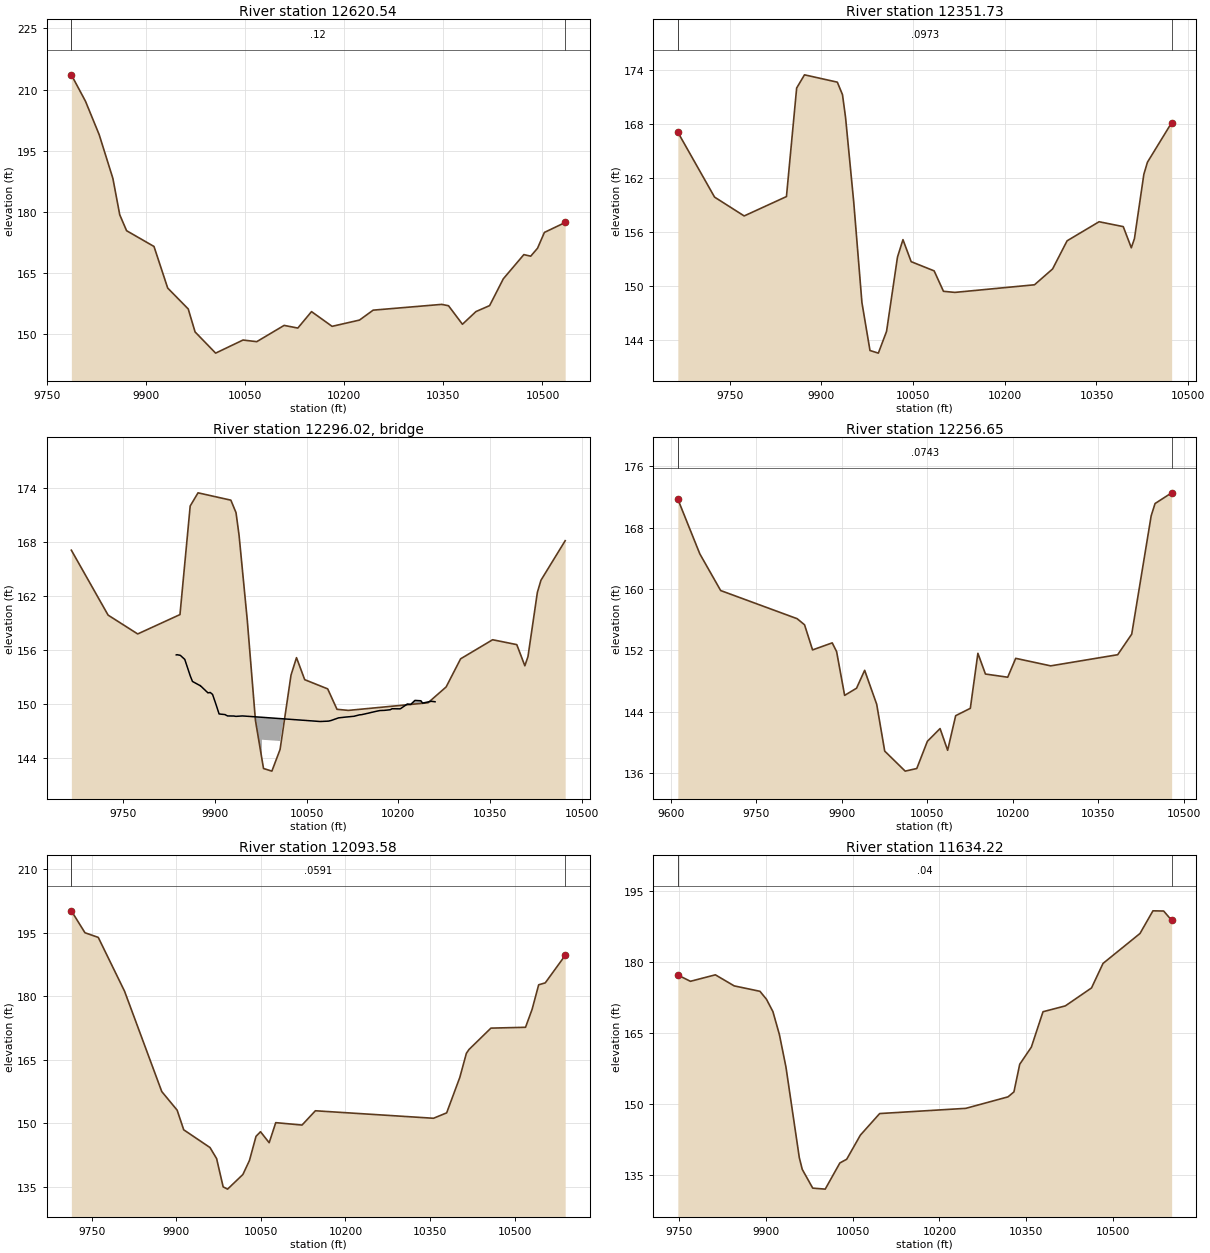
Type RM Length L Ch R = 1 ,12620.54,268.808400,268.808400,268.808400
XS GIS Cut Line= 2
439475.643334508759487.674858212 438754.68128264 759686.32728827
#Sta/Elev= 30
9786.578213.61499807.991 207.1339828.736198.93239849.482188.20269859.854179.2986
9870.227175.38749911.718171.52529932.463161.32829963.581156.19479973.954150.5621
10005.07145.367610046.56148.579110067.31148.1768 10108.8152.167610129.54151.5168
10150.29155.549910181.41151.9367 10222.9153.472310243.64155.906410347.37 157.321
10357.74156.987910378.83152.446310399.23155.551810419.98157.021910440.72163.5938
10471.84169.528610482.21169.139810492.59171.104210502.96174.971310534.41177.4022
#Mann= 3 , 0 , 0
9786.578    0.12       09786.578    0.12       010534.41    0.12       0
#XS Ineff= 2 , 0
       0                10282.89       0
Bank Sta=9786.578,10534.41
Exp/Cntr=0.3,0.1

Type RM Length L Ch R = 1 ,12351.73,95.080800,95.080800,95.080800
XS GIS Cut Line= 5
439394.655241042759124.890656352439238.837779045759231.164441541
439056.546112299759394.358885989438882.502463192759505.229198009
438754.898296535759614.604198009
#Sta/Elev= 30
9665.236167.11419725.341159.88219773.758157.78389842.904 159.9429859.595172.0348
9872.417173.50579926.104172.68919934.557171.29819939.526168.78759952.948159.3292
 9966.37148.12519979.534142.79219993.213142.500510006.64144.921510024.51153.2014
10033.48155.1423 10046.9152.689710084.48151.663910099.71 149.38810118.32149.2658
10248.61150.1144 10278.2151.877310301.91155.013310354.26157.138310393.78156.5941
10406.95154.237710412.08155.258910427.45162.417410433.29163.763410472.93168.1716
#Mann= 3 , 0 , 0
9665.236  0.0973       09665.236  0.0973       010472.93  0.0973       0
#XS Ineff= 2 , 0
       09953.562        10251.95       0
Bank Sta=9665.236,10472.93
Exp/Cntr=0.3,0.1

Type RM Length L Ch R = 3 ,12296.02,,,
BEGIN DESCRIPTION:
END DESCRIPTION:
Bridge Culvert--1,0,-1,-1, 0
Deck Dist Width WeirC Skew NumUp NumDn MinLoCord MaxHiCord MaxSubmerge Is_Ogee
38.010400,19.060000,2.6,0, 52, 52, , , 0.95, 0, 0,0,,
 9836.82 9838.07 9843.42 9850.70 9859.78 9863.34 9875.97 9876.14 9888.61 9892.50
 9896.22 9902.00 9906.87 9916.52 9920.66 9931.04 9934.45 9944.86 9976.89 9976.89
10051.9710051.9710071.7810072.3410076.2910085.3410086.2910090.0410102.5110103.03
10114.9710119.7710127.4410136.5110139.9110152.3810153.2510164.8510169.9910177.32
10186.7310189.7910202.2610203.4710214.7310220.2110227.2010236.9510239.6710252.14
10253.6910260.04
  155.45  155.47  155.40  154.95  153.09  152.49  152.02  152.03  151.22  151.26
  151.04  149.89  148.87  148.80  148.65  148.64  148.60  148.65  148.50  148.50
  148.13  148.13  148.03  148.03  148.04  148.07  148.08  148.14  148.44  148.44
  148.53  148.56  148.61  148.77  148.79  148.98  149.00  149.18  149.25  149.27
  149.34  149.45  149.44  149.45  149.98  149.93  150.38  150.34  150.08  150.26
  150.28  150.23
 -844.55 -844.53 -844.60 -845.05 -846.91 -847.51 -847.98 -847.97 -848.78 -848.74
 -848.96 -850.11 -851.13 -851.20 -851.35 -851.36 -851.40 -851.35 -851.50  146.00
  145.63 -851.87 -851.97 -851.97 -851.96 -851.93 -851.92 -851.86 -851.56 -851.56
 -851.47 -851.44 -851.39 -851.23 -851.21 -851.02 -851.00 -850.82 -850.75 -850.73
 -850.66 -850.55 -850.56 -850.55 -850.02 -850.07 -849.62 -849.66 -849.92 -849.74
 -849.72 -849.77
 9836.82 9838.07 9843.42 9850.70 9859.78 9863.34 9875.97 9876.14 9888.61 9892.50
 9896.22 9902.00 9906.87 9916.52 9920.66 9931.04 9934.45 9944.86 9969.74 9969.74
10044.8210044.8210071.7810072.3410076.2910085.3410086.2910090.0410102.5110103.03
10114.9710119.7710127.4410136.5110139.9110152.3810153.2510164.8510169.9910177.32
10186.7310189.7910202.2610203.4710214.7310220.2110227.2010236.9510239.6710252.14
10253.6910260.04
  155.45  155.47  155.40  154.95  153.09  152.49  152.02  152.03  151.22  151.26
  151.04  149.89  148.87  148.80  148.65  148.64  148.60  148.65  148.53  148.53
  148.16  148.16  148.03  148.03  148.04  148.07  148.08  148.14  148.44  148.44
  148.53  148.56  148.61  148.77  148.79  148.98  149.00  149.18  149.25  149.27
  149.34  149.45  149.44  149.45  149.98  149.93  150.38  150.34  150.08  150.26
  150.28  150.23
 -844.55 -844.53 -844.60 -845.05 -846.91 -847.51 -847.98 -847.97 -848.78 -848.74
 -848.96 -850.11 -851.13 -851.20 -851.35 -851.36 -851.40 -851.35 -851.47  146.03
  145.66 -851.84 -851.97 -851.97 -851.96 -851.93 -851.92 -851.86 -851.56 -851.56
 -851.47 -851.44 -851.39 -851.23 -851.21 -851.02 -851.00 -850.82 -850.75 -850.73
 -850.66 -850.55 -850.56 -850.55 -850.02 -850.07 -849.62 -849.66 -849.92 -849.74
 -849.72 -849.77
Pier Skew, UpSta & Num, DnSta & Num=  ,10014.43, 2 ,10007.28, 2 , 0 , 0 , 0 ,,
    3.00    3.00
 -851.69  148.31
    3.00    3.00
 -851.65  148.35
BR Coef=-1 , 0 , 0 ,, 0 ,,,0.8,0,1,0,
WSPro=,,,, 1 ,,,, 0 ,,,, 0 ,,,,-1 ,-1 ,-1 , 0 , 0 , 0 , 0 , 0
BC Design=,, 0 ,, 0 ,,,,,,

Type RM Length L Ch R = 1 ,12256.65,163.073200,163.073200,163.073200
XS GIS Cut Line= 5
439356.677810431759022.894128561439179.810001224759146.094997093
 439021.82389006759302.344997078438872.518334597759432.553330451
438703.683018774759589.430586889
#Sta/Elev= 30
9612.489171.70219651.094164.57139687.655159.79749821.711156.13499834.801155.3419
9848.866152.06699883.363 152.984 9891.06151.84329905.124146.14529926.025 147.081
9940.246149.41099961.383144.98549975.448138.891610011.35136.282710031.71136.6241
10050.24140.159810072.56141.825710085.83138.997910099.92143.502610125.64144.4603
 10138.9151.624110152.17148.925110191.21148.511110205.25150.970310266.63149.9896
10384.16 151.44210408.76154.119610442.92169.540710449.71171.127310478.81172.5215
#Mann= 3 , 0 , 0
9612.489  0.0743       09612.489  0.0743       010478.81  0.0743       0
#XS Ineff= 2 , 0
       09948.883        10218.76       0
Bank Sta=9612.489,10478.81
Exp/Cntr=0.3,0.1

Type RM Length L Ch R = 1 ,12093.58,459.359200,459.359200,459.359200
XS GIS Cut Line= 2
439067.398296565758934.048642442438617.310001224759685.331108198
#Sta/Elev= 30
 9713.98200.12029738.104194.95219761.718193.85189808.347181.15629874.311157.5031
9901.604153.10629913.262148.47979959.891144.29189971.548141.69659983.205135.0265
 9991.06 134.48810018.18137.938810029.83141.245710041.49146.941910049.43148.0208
10064.81 145.43610076.46150.166410123.09149.595910146.73152.966510356.24151.2004
10379.55152.471310402.87160.824110414.52166.511110419.14167.408810458.06172.4575
10519.44172.6547 10531.1176.887310542.75182.676610554.41183.126510589.77189.6093
#Mann= 3 , 0 , 0
 9713.98  0.0591       0 9713.98  0.0591       010589.77  0.0591       0
#XS Ineff= 2 , 0
       09892.299        10164.01       0
Bank Sta=9713.98,10589.77
Exp/Cntr=0.3,0.1

Type RM Length L Ch R = 1 ,11634.22,459.359200,459.359200,459.359200
XS GIS Cut Line= 6
438395.552693099758924.441017076438469.142467648759092.072563484
438600.164863616759311.536808357438640.124503881759417.713528737
438641.529365063759516.055299371438548.804500997759693.861741841
#Sta/Elev= 30
9748.234177.23269770.008175.90419813.065177.27329845.585174.93699890.034173.7913
9901.227172.12119912.419169.50339923.611164.65249934.912157.80659958.039138.6112
9963.104136.15179981.167132.192310002.73131.980110028.02137.510410039.82138.2954
10063.44 143.39210096.74147.949610245.57 149.056 10318.4151.482210328.57152.5262
10338.61 158.37510358.63161.987810378.81169.4749 10417.3170.704310462.58174.5059
10482.43179.683310546.22 186.00610568.61190.800410587.14190.759610600.92 188.792
#Mann= 3 , 0 , 0
9748.234    0.04       09748.234    0.04       010600.92    0.04       0
#XS Ineff= 2 , 0
       0                10129.21       0
Bank Sta=9748.234,10600.92
Exp/Cntr=0.3,0.1

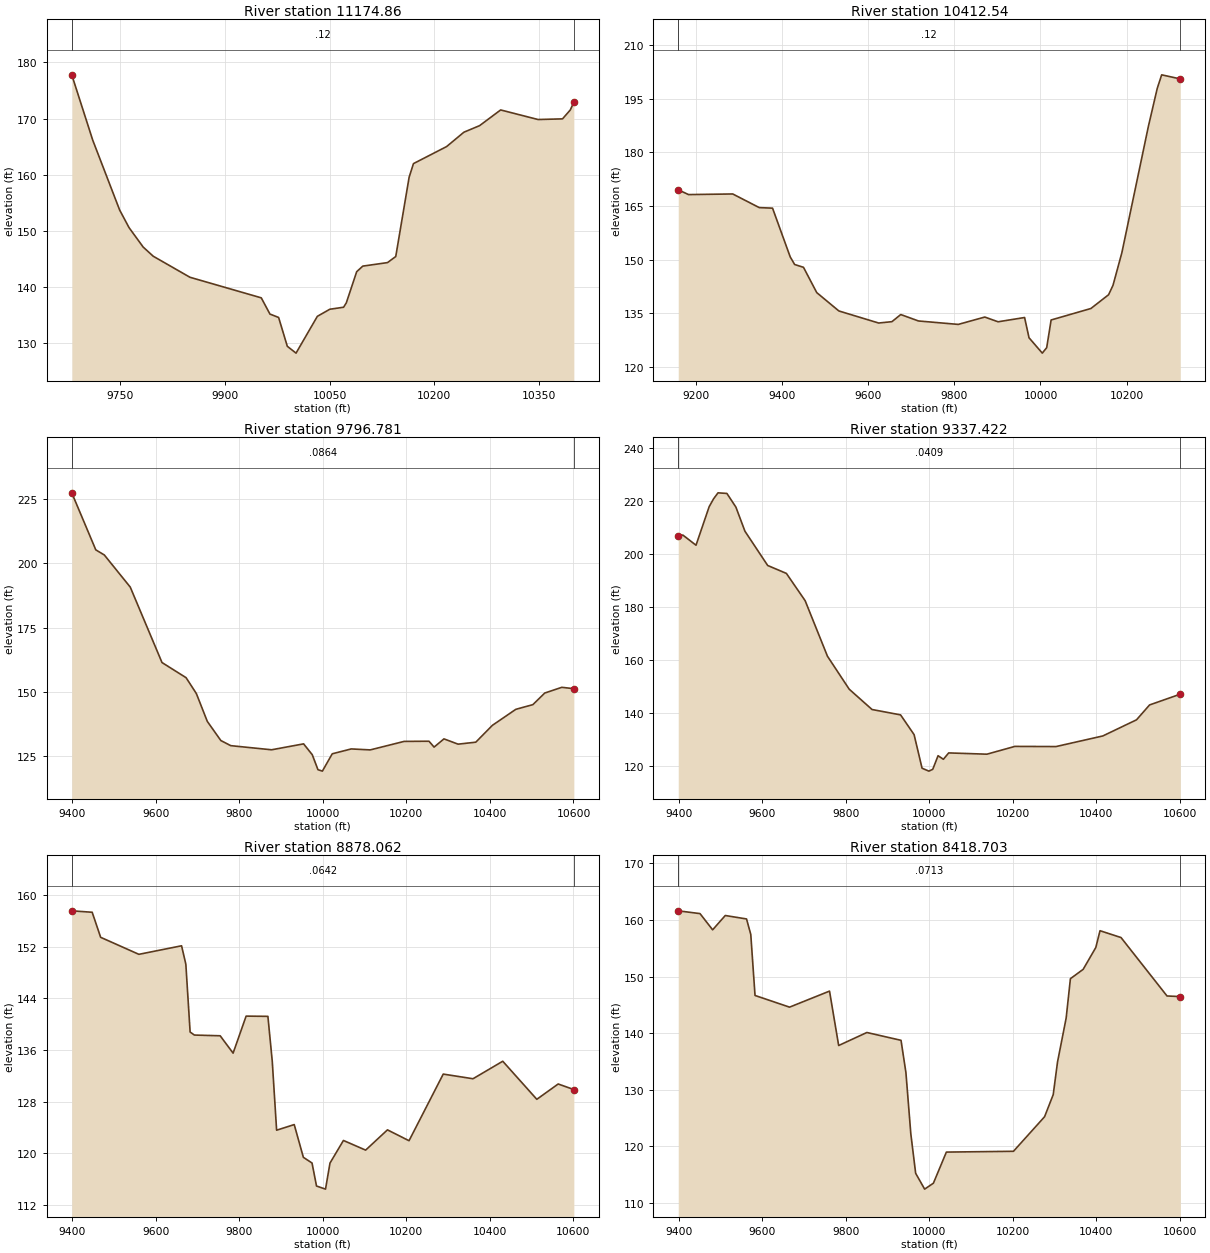
Type RM Length L Ch R = 1 ,11174.86,762.317000,762.317000,762.317000
XS GIS Cut Line= 6
437950.192695826759260.635075092438023.669428647759348.809545547
438106.334479719759419.038570821438390.118847281759614.324238256
 438449.71478343759670.549076527438485.462730676759729.566002131
#Sta/Elev= 30
9680.611177.78459710.715166.12199749.231153.69369762.749150.54519782.973147.0914
 9797.39145.45689850.066141.70699952.181138.04559964.617135.15369977.053134.5488
9989.489129.414510002.01128.194210032.54134.748510050.41136.014510070.12136.3708
10074.04137.148610088.91142.700510097.66143.6989 10133.1144.324710144.91145.4104
10164.06159.526910170.27161.963310217.82165.0014 10242.5167.5553   10265168.7248
10295.23171.526310348.84  169.8210383.87169.935810395.02171.522110400.12172.9106
#Mann= 3 , 0 , 0
9680.611    0.12       09680.611    0.12       010400.12    0.12       0
#XS Ineff= 2 , 0
       0                               0
Bank Sta=9680.611,10400.12
Exp/Cntr=0.3,0.1

Type RM Length L Ch R = 1 ,10412.54,615.760700,615.760700,615.760700
XS GIS Cut Line= 2
437902.118306071759211.729929894437641.701639444760347.146596551
#Sta/Elev= 30
9159.509169.49759183.383168.1557 9285.98168.32959347.538 164.5149378.317164.3628
9419.355150.73619429.615148.61069450.134147.82989480.913140.75469532.212135.6307
9624.548132.25819655.327132.63989675.847134.63049716.885132.83319809.222 131.874
 9870.78 133.9289901.559 132.6059963.117133.79919973.377128.140210004.16 123.846
10014.42125.381310024.67133.109310117.01136.319310158.05140.171910168.31142.8203
10188.83151.918610250.39187.248810270.91197.841310281.17201.626710324.41200.4797
#Mann= 3 , 0 , 0
9159.509    0.12       09159.509    0.12       010324.41    0.12       0
#XS Ineff= 2 , 0
       0                               0
Bank Sta=9159.509,10324.41
Exp/Cntr=0.3,0.1

Type RM Length L Ch R = 1 ,9796.781,459.359200,459.359200,459.359200
XS GIS Cut Line= 6
437697.543058274759098.641122469 437643.27800315759291.433109302
437558.516000608759415.895447816437455.603555928759498.486793773
437088.827463079759716.721364984436879.277293511759916.826037556
#Sta/Elev= 30
9399.113227.51759456.619 205.2959477.026203.29869539.138190.77489615.111161.3789
9672.777155.47439697.304149.30969723.596138.43119755.966130.98719779.654128.9931
9877.414127.38079954.045129.6873 9974.76125.47029988.441119.6215    9999119.0649
10022.62125.8171 10068.1127.713910113.58127.337210194.64130.647310254.22130.7153
10266.41128.424810290.01131.631310323.92129.574610366.21130.343310405.91136.9005
10462.05 143.14910502.83144.970910531.32149.495710572.11151.725810600.94151.1912
#Mann= 3 , 0 , 0
9399.113  0.0864       09399.113  0.0864       010600.94  0.0864       0
#XS Ineff= 2 , 0
       0                10269.47       0
Bank Sta=9399.113,10600.94
Exp/Cntr=0.3,0.1

Type RM Length L Ch R = 1 ,9337.422,459.359200,459.359200,459.359200
XS GIS Cut Line= 6
437406.942613512758644.452507841437336.526664431758836.737777792
437236.764434017759015.373763441437068.002308689759237.500144822
 436862.82331778759472.879621452436746.915308202759636.728102002
#Sta/Elev= 30
9399.084206.78279410.155207.06659441.643203.23229473.131217.75859483.655 220.713
9494.305222.98049515.605222.74529537.099217.60299558.775208.50679613.251 195.594
9657.994192.60839702.868182.33429756.296 161.3969808.373 148.9669863.041141.3113
9931.323139.28539963.673131.85219982.738119.1914    9999118.090510008.36118.7791
10021.07123.904210033.79122.557910046.51124.955110137.99 124.47510204.84127.4076
10303.36127.348710415.37131.340310496.15137.431610527.29143.027610600.94147.1055
#Mann= 3 , 0 , 0
9399.084  0.0409       09399.084  0.0409       010600.94  0.0409       0
#XS Ineff= 2 , 0
       0 9911.24        10360.49       0
Bank Sta=9399.084,10600.94
Exp/Cntr=0.3,0.1

Type RM Length L Ch R = 1 ,8878.062,459.359200,459.359200,459.359200
XS GIS Cut Line= 6
436852.594566498758416.858974307436814.871921782758622.512627869
 436771.78613464758806.482937357436740.775850053758911.159183867
436648.421566598759176.243923189436565.825883968 759581.63768948
#Sta/Elev= 30
9399.031157.53719447.883157.31619468.179153.43799559.732150.80389661.882152.1262
9672.124149.27139682.365138.77379692.607138.31019754.312138.19789785.252135.5117
9816.407141.24139868.555141.20489878.985134.25829889.414123.58359931.564124.4551
9953.453119.38719974.185118.50829984.955114.946610006.48114.4653 10017.2118.4968
10049.36121.996510102.53120.502310154.77123.638110206.42 121.957 10288.3132.2685
10359.54131.547610430.78134.258410512.33128.364910563.48130.736910600.96129.8765
#Mann= 3 , 0 , 0
9399.031  0.0642       09399.031  0.0642       010600.96  0.0642       0
#XS Ineff= 2 , 0
       09903.423        10248.32       0
Bank Sta=9399.031,10600.96
Exp/Cntr=0.3,0.1

Type RM Length L Ch R = 1 ,8418.703,459.359200,459.359200,459.359200
XS GIS Cut Line= 6
436116.845214334758463.282290149436145.497500468758653.169284506
436185.842266536758788.644390652436422.287489484759269.073956464
436452.775765898759430.145335782436454.250354946759596.809452666
#Sta/Elev= 30
 9399.12161.61149451.242161.11959481.477158.25329511.711160.78459562.571160.1741
9572.752157.44659582.934146.64999665.591144.58459761.246147.41999783.137137.8027
9850.639140.10279932.407138.7209 9944.13133.00479955.854 122.1789967.432115.2092
9988.938112.415610009.89113.461610040.96 118.96310201.53119.103310276.02125.2137
10296.69129.115810307.02134.898910327.67142.656710337.86149.617710368.35151.2651
10398.62155.1257 10408.7158.095510458.98156.888210569.07146.5594 10600.9146.4494
#Mann= 3 , 0 , 0
 9399.12  0.0713       0 9399.12  0.0713       0 10600.9  0.0713       0
#XS Ineff= 2 , 0
       09915.384                       0
Bank Sta=9399.12,10600.9
Exp/Cntr=0.3,0.1

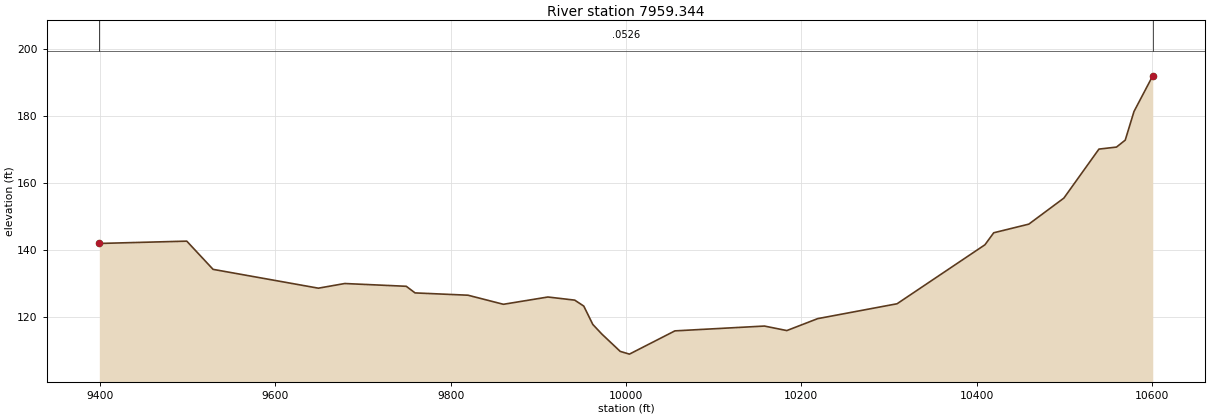
Type RM Length L Ch R = 1 ,7959.344,459.359300,459.359300,459.359300
XS GIS Cut Line= 6
435863.836341531758665.283220436435889.882578911759095.002947388
435951.839687311759365.926620435435977.234397615759530.757226219
435989.400330583759699.859343338435989.374666335759856.384493044
#Sta/Elev= 30
9399.031141.98919498.791142.67749528.804134.26269648.948128.64949679.034130.0401
9749.236129.21169759.292127.23989819.664126.55339860.061123.84429910.839126.0154
9941.441125.08629951.765123.30869962.088 117.8299972.412114.96019993.342109.8002
10003.85108.981110055.77115.917510157.86117.353910183.44116.006310218.59119.5611
10309.22124.0012 10409.5141.596110419.51 145.17510459.55147.750410499.55 155.515
10539.56170.129410559.56170.732610569.56172.804310579.56181.349910600.95191.9853
#Mann= 3 , 0 , 0
9399.031  0.0526       09399.031  0.0526       010600.95  0.0526       0
#XS Ineff= 2 , 0
       0 9905.52                       0
Bank Sta=9399.031,10600.95
Exp/Cntr=0.3,0.1