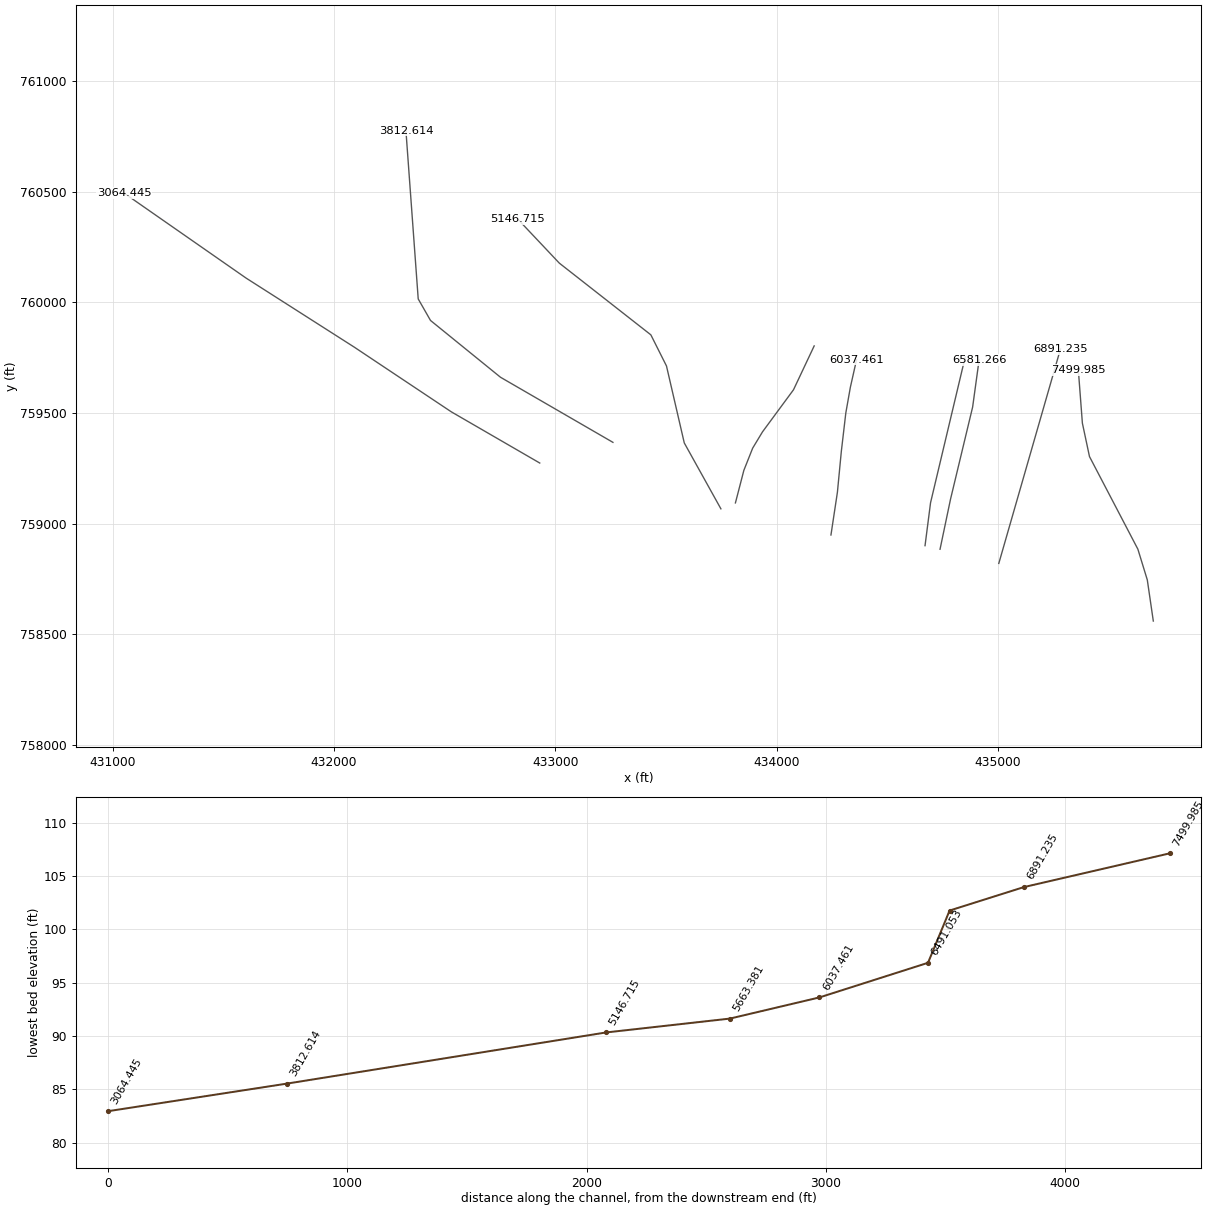
HEC-RAS study 2742_ras.prj: 2742

--- 2742_ras.g01 (geometry) --- (continued)

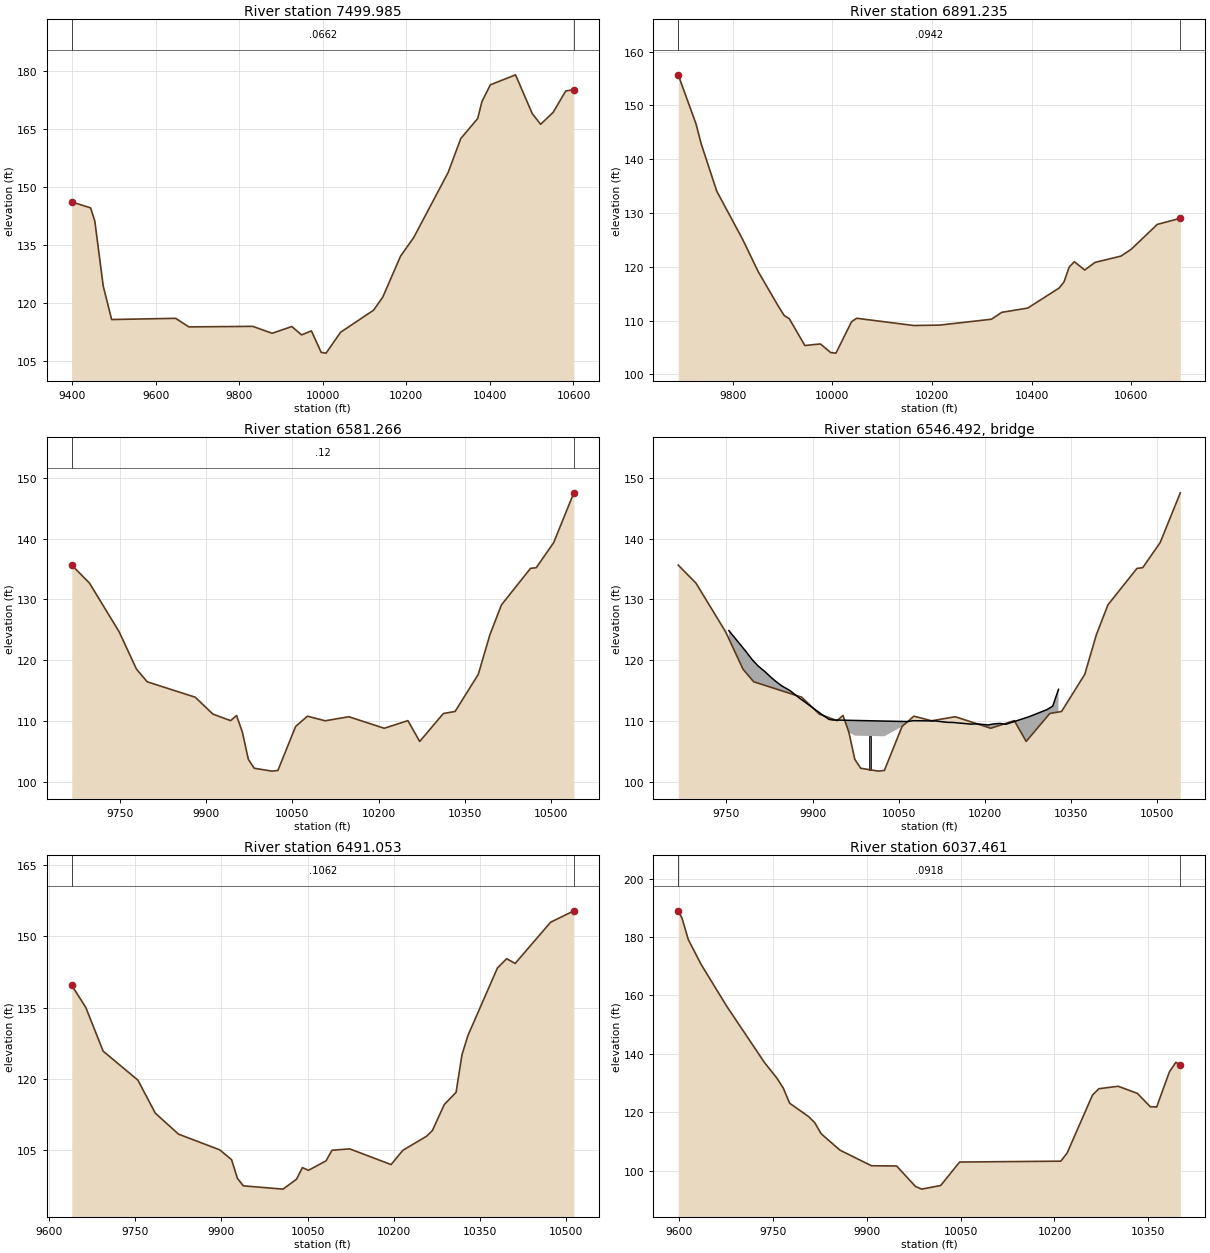
Type RM Length L Ch R = 1 ,7499.985,608.749100,608.749100,608.749100
XS GIS Cut Line= 6
435701.792119778 758560.26555608435674.648109913758746.157462562
435632.078177549758885.002832294435413.369171889759303.546035037
435381.310747331759454.365985633435363.037087782759694.367357548
#Sta/Elev= 30
  9399.1146.22849444.151   144.79454.222141.31919474.364124.49959494.506115.8188
9647.811116.12779679.476113.9128 9832.34114.05389878.821112.25979925.766114.0098
9949.239111.84589972.712 112.8849996.185107.302410007.89107.128510042.45112.5176
10121.38118.219810143.44121.593810186.04132.196610217.63137.037910299.84153.8135
 10330.3162.6263 10370.8167.822510380.86172.171210400.97176.514810461.29179.1044
10501.38 169.07410521.41166.310410551.45169.419710581.49174.928610600.89175.2492
#Mann= 3 , 0 , 0
  9399.1  0.0662       0  9399.1  0.0662       010600.89  0.0662       0
#XS Ineff= 2 , 0
       09859.996                       0
Bank Sta=9399.1,10600.89
Exp/Cntr=0.3,0.1

Type RM Length L Ch R = 1 ,6891.235,309.969300,309.969300,309.969300
XS GIS Cut Line= 2
435003.608468115758820.670902103435282.254301429759789.420902103
#Sta/Elev= 30
9690.475 155.6939726.196146.56559736.602142.85939767.861134.06069819.845125.0998
9851.062119.11299892.684112.48959903.089110.97169913.494110.35899944.711105.3819
9975.927105.67449996.738104.067210007.14103.966410038.36109.795610048.77110.4464
10163.23109.099810215.25109.173710319.31110.266110340.12111.546510392.15 112.342
 10455.2116.069810464.98117.198210475.39119.959510485.79120.961810506.61119.4119
10527.42120.835210579.44122.002210599.91123.269110652.28127.8947 10698.5129.0269
#Mann= 3 , 0 , 0
9690.475  0.0942       09690.475  0.0942       0 10698.5  0.0942       0
#XS Ineff= 2 , 0
       0                               0
Bank Sta=9690.475,10698.5
Exp/Cntr=0.3,0.1

Type RM Length L Ch R = 1 ,6581.266,90.213000,90.213000,90.213000
XS GIS Cut Line= 4
434738.080432445758884.717855677434785.381858528759110.595658287
434885.381858528759527.262324944434914.548525244759739.762324944
#Sta/Elev= 30
9666.038135.64489696.977 132.6739748.586124.66199778.712118.53219797.375116.4588
9880.881113.92479911.628111.1481 9942.48110.06819952.764 110.9259963.048108.1462
9973.332 103.7119983.616  102.2410014.47101.769110024.75101.8785 10055.6  109.11
10076.17110.804210107.02110.046410148.16110.712810209.86 108.817   10251110.0712
10271.57106.6502 10312.7111.243710333.12111.5763 10373.5117.676810393.69124.1902
10413.87129.111810464.34135.099310474.44135.225610504.72139.346110539.81147.5291
#Mann= 3 , 0 , 0
9666.038    0.12       09666.038    0.12       010539.81    0.12       0
#XS Ineff= 2 , 0
       0 9942.19        10242.82       0
Bank Sta=9666.038,10539.81
Exp/Cntr=0.3,0.1

Type RM Length L Ch R = 3 ,6546.492,,,
BEGIN DESCRIPTION:
END DESCRIPTION:
Bridge Culvert--1,0,-1,-1, 0
Deck Dist Width WeirC Skew NumUp NumDn MinLoCord MaxHiCord MaxSubmerge Is_Ogee
27.801500,34.610000,2.6,0, 30, 28, , , 0.95, 0, 0,0,,
 9754.12 9784.47 9794.75 9805.03 9817.60 9825.60 9835.88 9846.16 9860.53 9877.01
 9918.14 9928.43 9934.63 9934.6310064.8010064.8010075.1710113.5210134.0810144.66
10174.9710185.1810205.5810214.5210225.9810236.1810276.9910307.5910317.7910327.87
  124.88  121.37  120.10  119.06  118.07  117.35  116.52  115.79  115.01  113.78
  110.94  110.28  110.18  110.18  109.92  109.92  110.06  110.02  109.79  109.77
  109.50  109.54  109.36  109.53  109.61  109.47  110.73  111.88  112.46  115.22
 -875.12 -878.63 -879.90 -880.94 -881.93 -882.65 -883.48 -884.21 -884.99 -886.22
 -889.06 -889.72 -889.82  107.68  107.42 -890.08 -889.94 -889.98 -890.21 -890.23
 -890.50 -890.46 -890.64 -890.47 -890.39 -890.53 -889.27 -888.12 -887.54 -884.78
 9754.12 9784.47 9794.75 9805.03 9835.88 9846.16 9860.53 9877.01 9928.15 9928.15
 9936.8210058.3210058.3210066.1410075.1710113.5210134.0810144.6610174.9710185.18
10205.5810214.5210225.9810236.1810276.9910307.5910317.7910327.87
  124.88  121.37  120.10  119.06  116.52  115.79  115.01  113.78  110.30  110.30
  110.14  109.93  109.93  109.92  110.06  110.02  109.79  109.77  109.50  109.54
  109.36  109.53  109.61  109.47  110.73  111.88  112.46  115.22
 -875.12 -878.63 -879.90 -880.94 -883.48 -884.21 -884.99 -886.22 -889.70  107.80
  107.64  107.43 -890.07 -890.08 -889.94 -889.98 -890.21 -890.23 -890.50 -890.46
 -890.64 -890.47 -890.39 -890.53 -889.27 -888.12 -887.54 -884.78
Pier Skew, UpSta & Num, DnSta & Num=  ,9999.71, 2 ,9993.23, 2 , 0 , 0 , 0 ,,
    3.00    3.00
 -889.97  110.03
    3.00    3.00
 -889.96  110.04
BR Coef=-1 , 0 , 0 ,, 0 ,,,0.8,0,1,0,
WSPro=,,,, 1 ,,,, 0 ,,,, 0 ,,,,-1 ,-1 ,-1 , 0 , 0 , 0 , 0 , 0
BC Design=,, 0 ,, 0 ,,,,,,

Type RM Length L Ch R = 1 ,6491.053,453.591800,453.591800,453.591800
XS GIS Cut Line= 3
434670.300598681758900.857041791 434695.25719592759095.084472328
434852.048525244759754.345658273
#Sta/Elev= 30
9639.688139.65929664.029135.02839694.276125.84319754.769119.74649785.016112.8193
9825.344108.41649897.099  105.129917.656103.05969927.93599.124169938.21497.55959
10007.2896.8681510030.7298.95785   10041101.397110051.28100.813210082.12102.8145
 10092.4105.034510123.23105.317810195.19102.025210215.75105.024910256.86107.9668
10267.14109.1864 10287.7 114.62210308.26117.190610318.53125.074210328.81129.0923
10380.21143.298110396.26145.252710411.04144.247410472.72152.905810513.16155.2996
#Mann= 3 , 0 , 0
9639.688  0.1062       09639.688  0.1062       010513.16  0.1062       0
#XS Ineff= 2 , 0
       09929.535        10222.28       0
Bank Sta=9639.688,10513.16
Exp/Cntr=0.3,0.1

Type RM Length L Ch R = 1 ,6037.461,374.080300,374.080300,374.080300
XS GIS Cut Line= 6
434245.178470509758949.070737385434274.369275083759142.381700768
434292.076569291 759327.09450028434312.367832342759500.708942273
434332.933714829759616.929615225 434361.03688562  759741.8601214
#Sta/Elev= 30
9599.015188.97129605.024186.46479615.157179.09079635.424170.67319675.957156.4548
9736.616137.04639756.803131.59429766.897128.1927 9776.99123.05119807.211118.4886
9817.257116.32939827.302112.6022 9857.44106.96329907.669101.63089947.853101.5521
 9977.9994.525039988.04893.6206510018.25 94.868510048.45102.900310210.03103.2002
10220.18 105.984 10260.8125.883410270.96128.023610301.69128.868210332.44126.4226
10352.94121.866310363.19121.762910383.69133.875210393.94137.051710400.97136.2041
#Mann= 3 , 0 , 0
9599.015  0.0918       09599.015  0.0918       010400.97  0.0918       0
#XS Ineff= 2 , 0
       0                               0
Bank Sta=9599.015,10400.97
Exp/Cntr=0.3,0.1

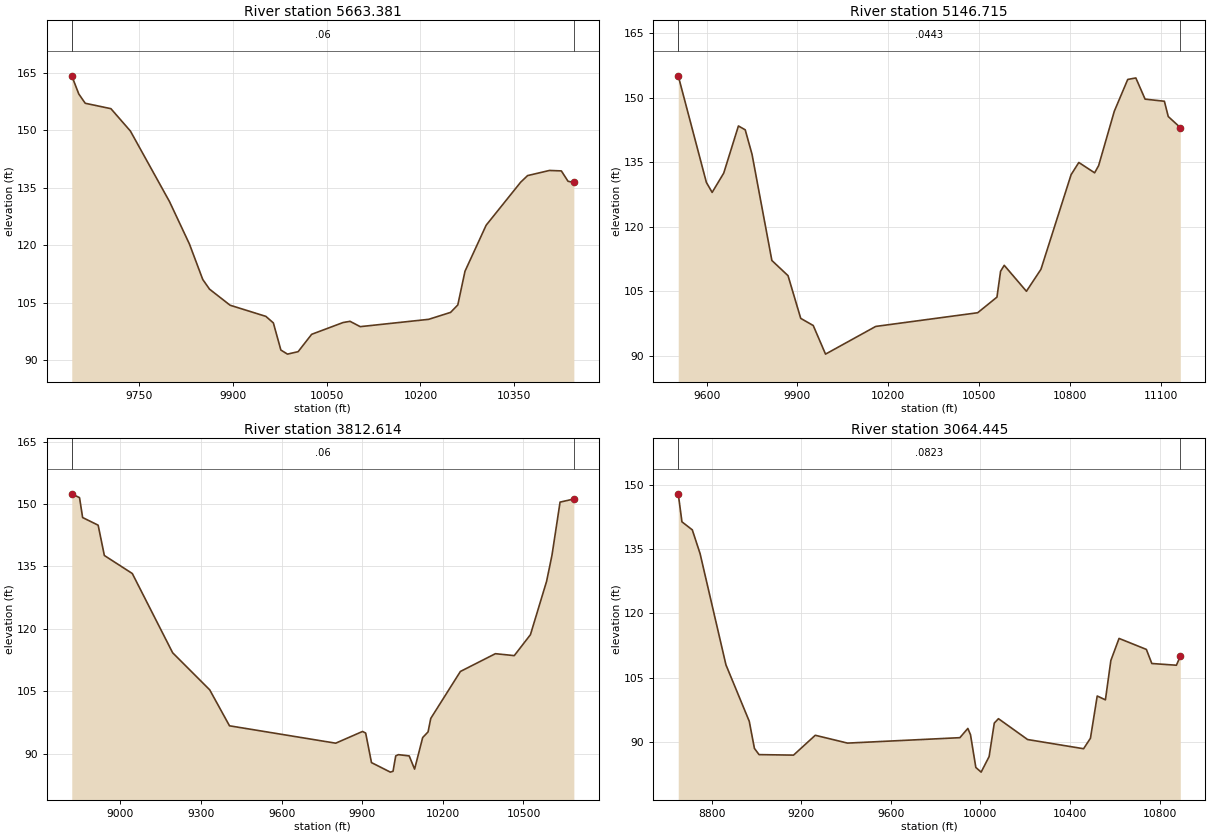
Type RM Length L Ch R = 1 ,5663.381,516.665800,516.665800,516.665800
XS GIS Cut Line= 6
433813.509561276759094.062802989 433851.63957718759241.289061609
433891.438970619759341.520009139433935.799137103759415.062132836
434075.984027865759605.356845791434169.430614134 759803.55520785
#Sta/Elev= 30
 9643.15164.14939654.376159.41639664.641157.00249705.698155.58789736.775149.7664
 9799.22131.39039831.092120.31969852.341111.09399863.159108.56439896.053104.3756
9953.157101.4732 9965.1399.765289977.10392.705019987.69791.63523 10004.792.27759
10026.2996.7960110076.5599.87195 10087.6100.181810103.8698.7946810213.16100.7006
 10248.2102.5139 10259.7104.4499 10271.2113.234910304.99 125.22610360.18136.4455
10371.15138.151810406.09139.492610425.07139.374610435.83136.660810445.04136.3877
#Mann= 3 , 0 , 0
 9643.15    0.06       0 9643.15    0.06       010445.04    0.06       0
#XS Ineff= 2 , 0
       0                               0
Bank Sta=9643.15,10445.04
Exp/Cntr=0.3,0.1

Type RM Length L Ch R = 1 ,5146.715,1334.101300,1334.101300,1334.101300
XS GIS Cut Line= 6
433747.903765053  759067.3396236433582.418790072759365.034070492
 433502.00043878759712.838726699433431.366102874759853.557528272
433017.795903087760177.535918504432830.304917872760376.178682536
#Sta/Elev= 30
9506.357155.13089599.273130.33069618.362127.9869 9656.54132.46719705.163143.4555
9727.612 142.561 9750.06136.87599815.641112.14199869.043108.60159910.97698.65945
9952.28896.99725 9992.8990.3368510158.7496.7851310495.4199.97122 10559.1 103.607
10571.13109.638310583.16111.013110656.46104.970510704.36110.078410804.04132.1218
10829.51134.951910881.74 132.55110894.93134.218410946.71146.880310991.09154.2901
11017.86154.633711048.44149.701711112.18149.212111124.95145.649611164.76143.0824
#Mann= 3 , 0 , 0
9506.357  0.0443       09506.357  0.0443       011164.76  0.0443       0
#XS Ineff= 2 , 0
       0                10666.99       0
Bank Sta=9506.357,11164.76
Exp/Cntr=0.3,0.1

Type RM Length L Ch R = 1 ,3812.614,748.168700,748.168700,748.168700
XS GIS Cut Line= 5
433259.982672721759367.767865717432751.907748878759661.916505858
432435.741717607 759918.51076144432380.186162055760015.732983649
432324.630606532 760776.14965032
#Sta/Elev= 30
8818.866152.47418847.733151.55058859.288146.77278917.063144.92948940.173 137.643
9044.168133.30549194.383114.24039332.266105.33119405.94696.67796 9801.2192.49713
 9901.2395.319929912.748 94.92999934.40187.8263410004.5985.5359810014.6185.74639
10024.64 89.441310034.6789.7383310074.77 89.431610094.8386.2649810124.91 93.8487
10144.9695.2109210154.9998.4493410265.28109.747310395.63114.022910465.81113.5581
10525.97118.591410586.13131.432410606.19137.713910636.27150.477810687.55151.2315
#Mann= 3 , 0 , 0
8818.866    0.06       08818.866    0.06       010687.55    0.06       0
#XS Ineff= 2 , 0
       09925.109        10412.35       0
Bank Sta=8818.866,10687.55
Exp/Cntr=0.3,0.1

Type RM Length L Ch R = 1 ,3064.445,0.000000,0.000000,0.000000
XS GIS Cut Line= 5
432929.331441968759274.292554864432529.685526669759505.666505858
432092.185526639759797.333172515431602.602193326  760109.8331725
431050.631449764 760494.24136891
#Sta/Elev= 30
 8651.05147.9262 8667.61141.3866 8713.83139.51238748.495133.97728864.045107.9941
 8968.0494.82551 8991.1588.484459011.71887.034419165.72386.917829262.69491.55061
9406.91689.722529908.17290.990879943.762 93.15449955.62691.673759979.353 84.0467
10003.0882.9468110038.6786.57719 10061.894.3973210080.3895.4229210210.48 90.5564
10460.27 88.409710490.9890.85488 10521.2100.722610557.7699.8236410582.13109.0207
10618.69114.164310740.55111.600310764.92108.3079 10874.6107.9049 10892.1109.9937
#Mann= 3 , 0 , 0
 8651.05  0.0823       0 8651.05  0.0823       0 10892.1  0.0823       0
#XS Ineff= 2 , 0
       09914.817        10095.45       0
Bank Sta=8651.05,10892.1
Exp/Cntr=0.3,0.1